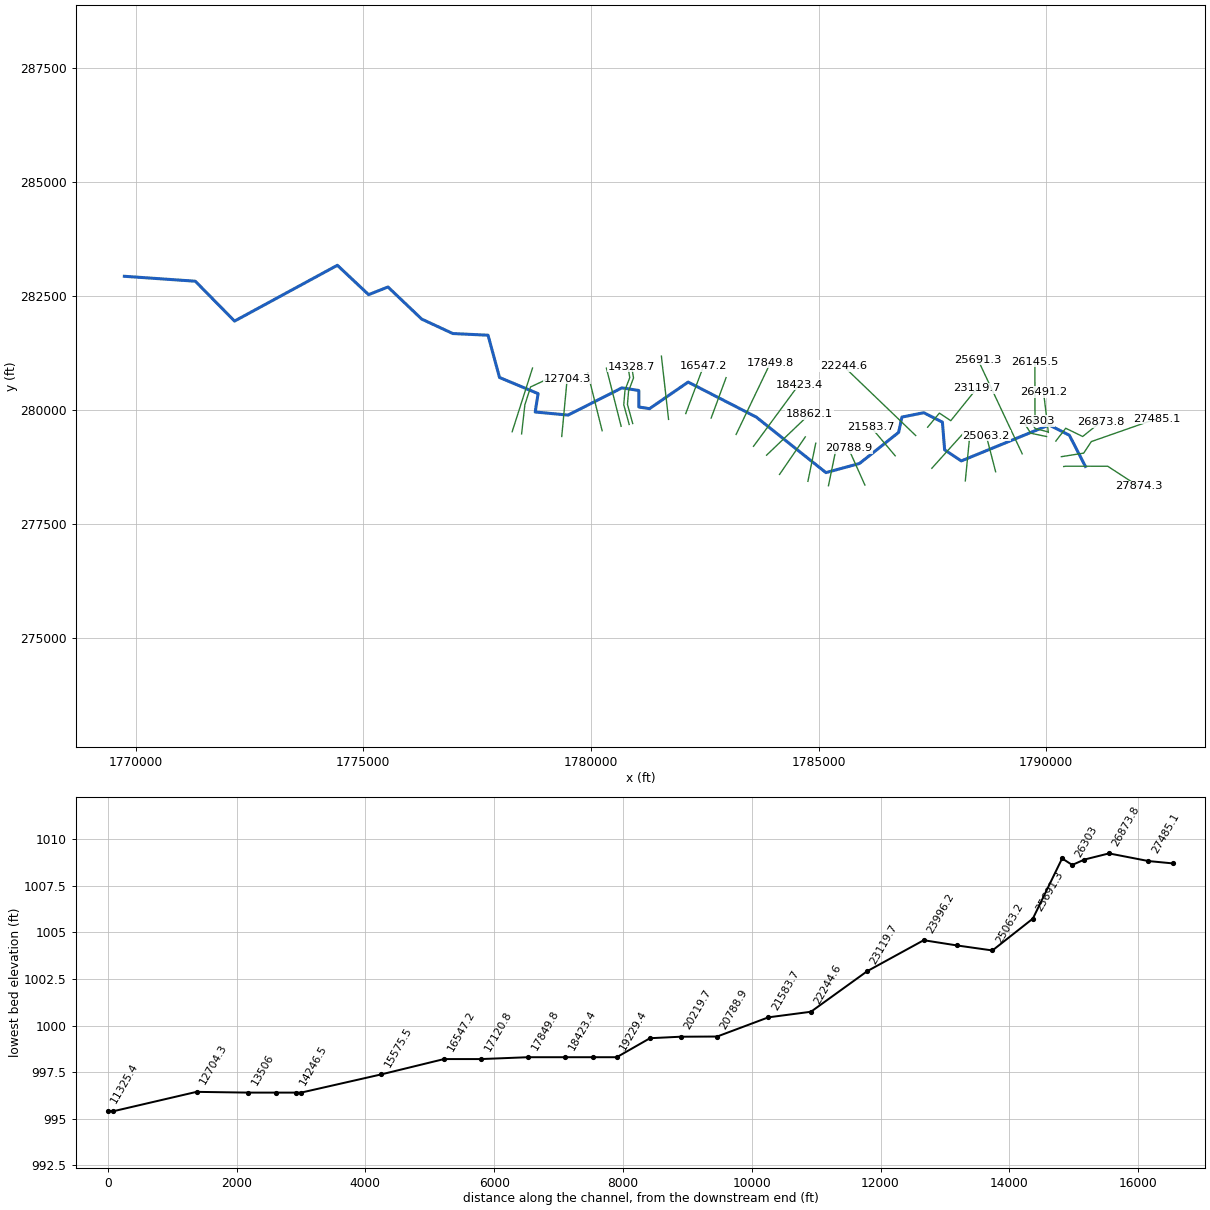
--- SimpsonCrk.prj (project) ---

Proj Title=SimpsonCrk
Current Plan=p01
Default Exp/Contr=0,0
English Units
Geom File=g01
Flow File=f01
Plan File=p01
BEGIN DESCRIPTION:
END DESCRIPTION:
DSS Export Rating Curves= 0
DSS Export Rating Curve Sorted= 0
DSS Export Volume Flow Curves= 0
DXF OffsetX= 0
DXF OffsetY= 0
DXF ScaleX= 0
DXF ScaleY= 0

--- SimpsonCrk.p01 (plan) ---

Plan Title=Floodplain
Program Version=4.00
Geom File=g01
Flow File=f01
K Sum by GR=0
Std Step Tol=0.01
Critical Tol=0.01
Num of Std Step Trials=20
Max Error Tol=0.3
Flow Tol Ratio=0.001
Split Flow NTrial=30
Split Flow Tol=0.02
Split Flow Ratio=0.02
Log Output Level=0
Friction Slope Method=1
Unsteady Friction Slope Method=2
Unsteady Bridges Friction Slope Method=1
Global Log Level=0
CheckData=False
Run HTab=0
Run UNet=0
Run PostProcess=0
UNET Theta=0
UNET Theta Warmup=0
UNET ZTol=0
UNET ZSATol=0
UNET MxIter=0
UNET MaxInSteps=0
UNET DtIC=0
UNET DtMin=0
UNET MaxCRTS=0
UNET WFStab=0
UNET SFStab=0
UNET WFX=0
UNET SFX=0
UNET DSS MLevel=0
UNET DZMax Abort=0
UNET Convert EG Bridges=0
UNET Use Existing IB Tables=0
UNET Froude Limit=0
UNET Froude Power=0
Write IC File=0
Echo Input=False
Echo Output=False
Write Detailed=0

--- SimpsonCrk.f01 (steady flow) ---

Flow Title=NFF Regression Equation
Program Version=4.00
Number of Profiles=1
Profile Names=P100yr
River Rch & RM=SimpsonCrk,Main      ,27874.3
    5281
River Rch & RM=SimpsonCrk,Main      ,19745.7
    5772
River Rch & RM=SimpsonCrk,Main      ,10417.7
    5971
River Rch & RM=SimpsonCrk,Main      ,1931.5
    6145
River Rch & RM=SimpsonCrk,Main      ,29.3
    6413
Boundary for River Rch & Prof#=SimpsonCrk,Main      ,1
Up Type=0
Dn Type=3
Dn Slope=0.000655

--- SimpsonCrk.g01 (geometry) ---

Geom Title=USGS 10m DEM
Program Version=4.10

River Reach=SimpsonCrk      ,Main
Reach XY= 30
      1790861.91      278759.729     1790508.767      279445.347
     1790064.391      279669.842     1788135.512      278880.376
     1787769.618      279124.409     1787720.826      279731.959
     1787311.743      279939.477     1786831.408      279843.099
     1786759.137      279506.664     1785899.232      278823.765
     1785162.254      278623.635     1783630.494      279844.551
     1782136.018      280612.055     1781287.035      280027.676
     1781053.172      280064.565      1781051.81       280427.68
      1780680.71      280484.985     1779499.201      279887.192
     1778777.123      279954.912      1778840.08      280358.422
     1777993.174      280712.931     1777741.132      281641.136
     1776967.107      281678.324      1776284.36      281995.217
     1775543.248      282700.756      1775117.65      282532.357
     1774431.899       283177.72     1772173.026      281951.719
     1771311.287      282827.586      1769752.41      282935.726

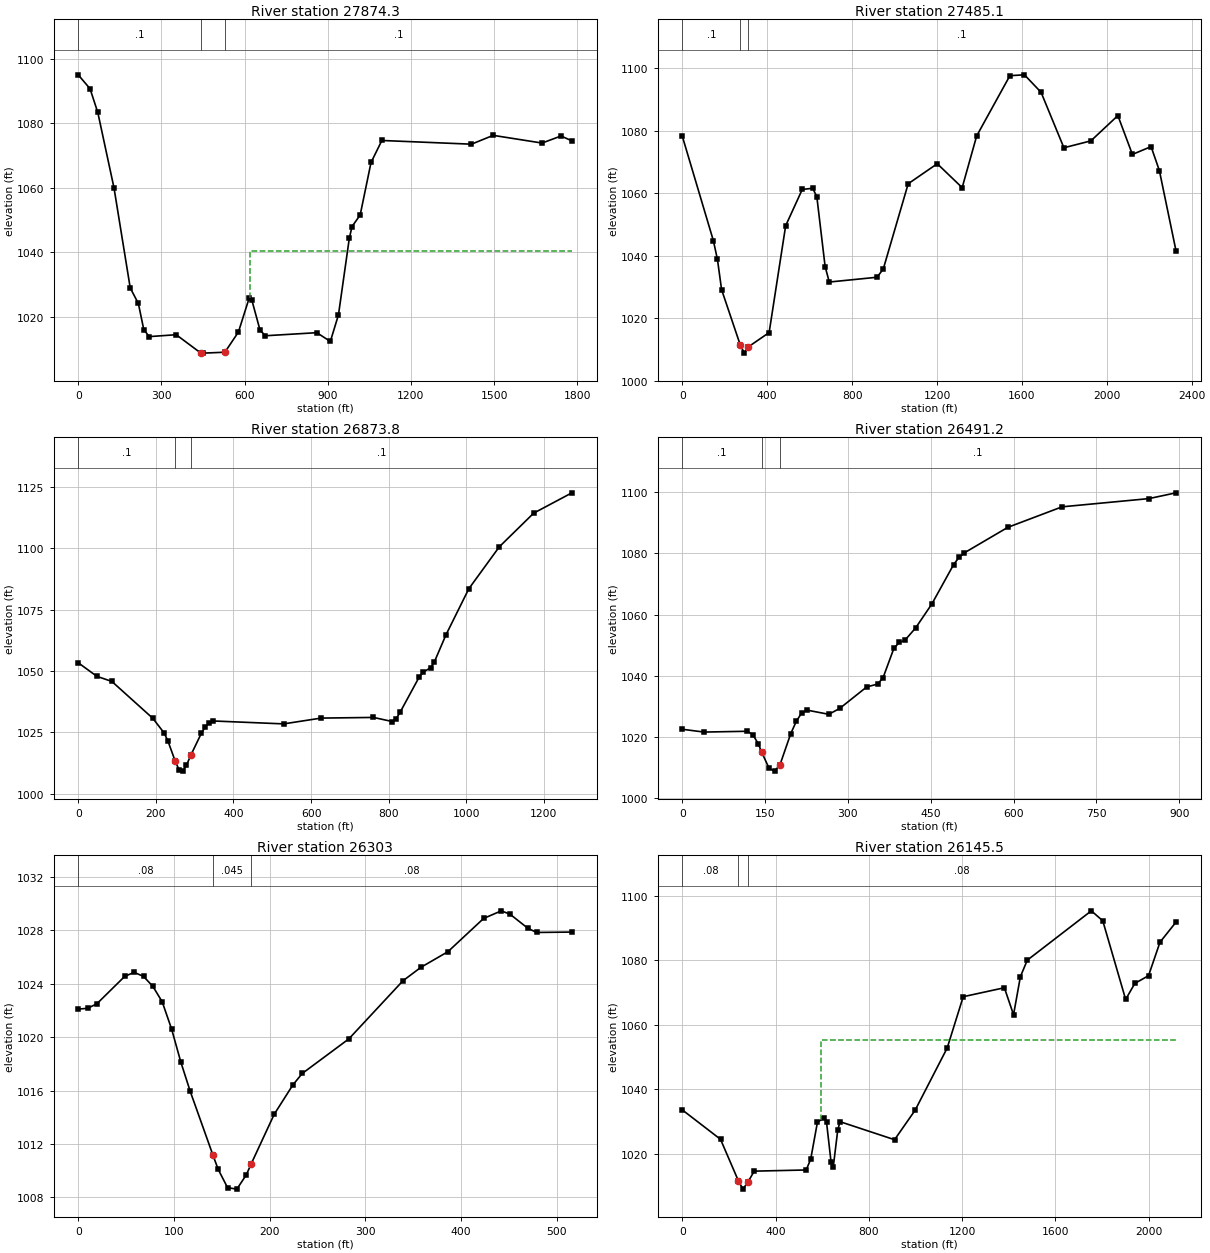
Type RM Length L Ch R = 1 ,27874.3 ,385,389.2,392.4
XS GIS Cut Line= 4
     1790384.714      278757.247      1790435.28      278764.318
     1791352.164      278763.233      1792033.24      278319.813
#Sta/Elev= 30
       0 1095.01    42.6  1090.7    70.6 1083.33   129.1 1059.93   187.6 1028.91
   216.9  1024.1   236.4 1016.02   255.9 1013.82   353.4 1014.41   441.2 1008.79
     451  1008.7     529 1008.98   577.8 1015.24   616.8 1025.84   626.6 1025.03
   655.8 1015.81   675.3 1014.09   860.6 1015.04   909.4 1012.32   938.7  1020.6
   977.7 1044.26   987.5 1047.96  1016.9 1051.52  1056.1 1067.82  1095.2 1074.65
  1418.4  1073.5  1496.7 1076.24  1672.9 1073.85  1741.5 1076.04  1780.6 1074.53
#Mann= 3 , 0 , 0
       0      .1       0   441.2    .045       0     529      .1       0
#XS Ineff= 2 , 0
                          618.07         1040.32
Permanent Ineff=
       F       F
Bank Sta=441.2,529
XS Rating Curve= 0 ,0
Exp/Cntr=0.3,0.1

Type RM Length L Ch R = 1 ,27485.1 ,582.4,611.4,640.2
XS GIS Cut Line= 4
     1790333.736      278973.464     1790824.187      279051.589
     1790991.103      279304.996     1792431.375      279808.843
#Sta/Elev= 30
       0 1078.25   146.1 1044.88   165.5 1038.84     185 1029.16   272.7  1011.5
   292.1 1008.83   310.41010.806     409 1015.41   486.9 1049.61   565.2 1061.24
   614.1  1061.6   633.7 1058.94   672.8 1036.55   692.4 1031.59   917.4 1033.12
   946.8 1035.76  1064.2 1063.05  1201.1 1069.46  1318.5 1061.81  1386.9 1078.37
  1543.4 1097.65  1611.9 1097.92  1690.2 1092.33  1797.8 1074.57  1924.9 1076.78
  2052.1 1084.87  2120.5 1072.44  2208.6 1074.94  2247.7 1067.25  2325.9 1041.62
#Mann= 3 , 0 , 0
       0      .1       0   272.7    .045       0   310.4      .1       0
Bank Sta=272.7,310.4
XS Rating Curve= 0 ,0
Exp/Cntr=0.3,0.1

Type RM Length L Ch R = 1 ,26873.8 ,355.3,382.5,409.8
XS GIS Cut Line= 4
     1790212.208      279316.346     1790429.222      279598.464
     1790801.703       279416.55     1791192.328       279731.22
#Sta/Elev= 30
       0 1053.38    48.1 1047.84    86.6 1045.78   192.4 1030.72   221.2 1024.81
   230.9 1021.62   250.1 1013.22   259.7 1009.83   269.4 1009.24     279 1011.65
   289.81015.625   317.4 1024.69   327.1 1027.18   336.7  1028.9   346.3 1029.68
   529.4 1028.48   625.9 1030.84   760.8 1031.11   809.8 1029.42   819.6 1030.66
   829.5 1033.24   878.6 1047.55   888.5 1049.54   908.2 1051.36     918 1053.83
   947.5 1064.71  1006.5 1083.52  1085.2 1100.63  1173.7 1114.32  1272.1 1122.59
#Mann= 3 , 0 , 0
       0      .1       0   250.1    .045       0   289.8      .1       0
Bank Sta=250.1,289.8
XS Rating Curve= 0 ,0
Exp/Cntr=0.3,0.1

Type RM Length L Ch R = 1 ,26491.2 ,141.8,188.3,233.7
XS GIS Cut Line= 2
     1790047.837      279506.848     1789942.252       280394.86
#Sta/Elev= 30
       0 1022.57    39.3 1021.66   117.9 1021.92   127.8  1020.8   137.6 1017.85
   143.51015.187   157.2 1009.84   167.1 1008.91   176.9 1010.98   196.5 1021.18
   206.4 1025.13   216.2 1027.91     226 1028.82   265.3 1027.46     285 1029.36
   334.1  1036.4   353.8 1037.32   363.6 1039.38   383.3    1049   393.1 1050.93
   402.9 1051.56   422.6 1055.64     452 1063.46   491.4  1076.3   501.2 1078.69
     511 1080.17   589.6 1088.48   687.9 1095.18   845.1 1097.86   894.3 1099.75
#Mann= 3 , 0 , 0
       0      .1       0   143.5    .045       0   176.9      .1       0
Bank Sta=143.5,176.9
XS Rating Curve= 0 ,0
Exp/Cntr=0.3,0.1

Type RM Length L Ch R = 1 ,26303   ,149.4,157.5,195.7
XS GIS Cut Line= 4
     1790030.662      279520.833     1789757.294      279592.854
     1789691.496      279696.036     1789783.266      279757.812
#Sta/Elev= 30
       0  1022.1     9.8 1022.16    19.5  1022.5    48.7 1024.56    58.5 1024.85
    68.2 1024.55      78  1023.8    87.7 1022.65    97.5 1020.62   107.2 1018.13
     117 1015.94   140.8 1011.15   146.2  1010.1     156 1008.73   165.7 1008.62
   175.5 1009.68   180.8 1010.53   204.7 1014.22   224.2 1016.42     234 1017.28
   282.7 1019.87   339.2 1024.22     358 1025.23   386.2  1026.4   423.5 1028.89
     442 1029.46   451.2  1029.2   469.6 1028.16   478.8 1027.84   515.7 1027.87
#Mann= 3 , 0 , 0
       0     .08       0   140.8    .045       0   180.8     .08       0
Bank Sta=140.8,180.8
XS Rating Curve= 0 ,0
Exp/Cntr=0.3,0.1

Type RM Length L Ch R = 1 ,26145.5 ,497.6,454.2,381.7
XS GIS Cut Line= 5
     1790009.092      279415.476     1789660.196      279488.967
     1789535.021      279685.264     1789753.884      279764.435
     1789752.966       281059.97
#Sta/Elev= 30
       0 1033.54   163.8 1024.43   240.9 1011.48   260.2 1008.97   282.61011.306
   308.4 1014.55   531.2 1014.91   550.6 1018.22   579.7 1029.77   608.8 1031.03
   618.5  1029.8   637.8 1017.52   647.6 1015.91   666.9 1027.39   676.6 1029.89
   910.4  1024.3   998.8 1033.47  1136.2 1052.75  1204.9 1068.66  1381.5 1071.44
  1420.8 1063.06  1450.2 1074.88  1479.7 1079.99  1754.5  1095.3  1803.6  1092.2
  1901.7 1067.81    1941 1072.78  1999.9 1075.19  2048.9 1085.56  2117.6 1091.79
#Mann= 3 , 0 , 0
       0     .08       0   240.9    .045       0   282.6     .08       0
#XS Ineff= 2 , 0
                          592.92         1055.38
Permanent Ineff=
       F       F
Bank Sta=240.9,282.6
XS Rating Curve= 0 ,0
Exp/Cntr=0.3,0.1

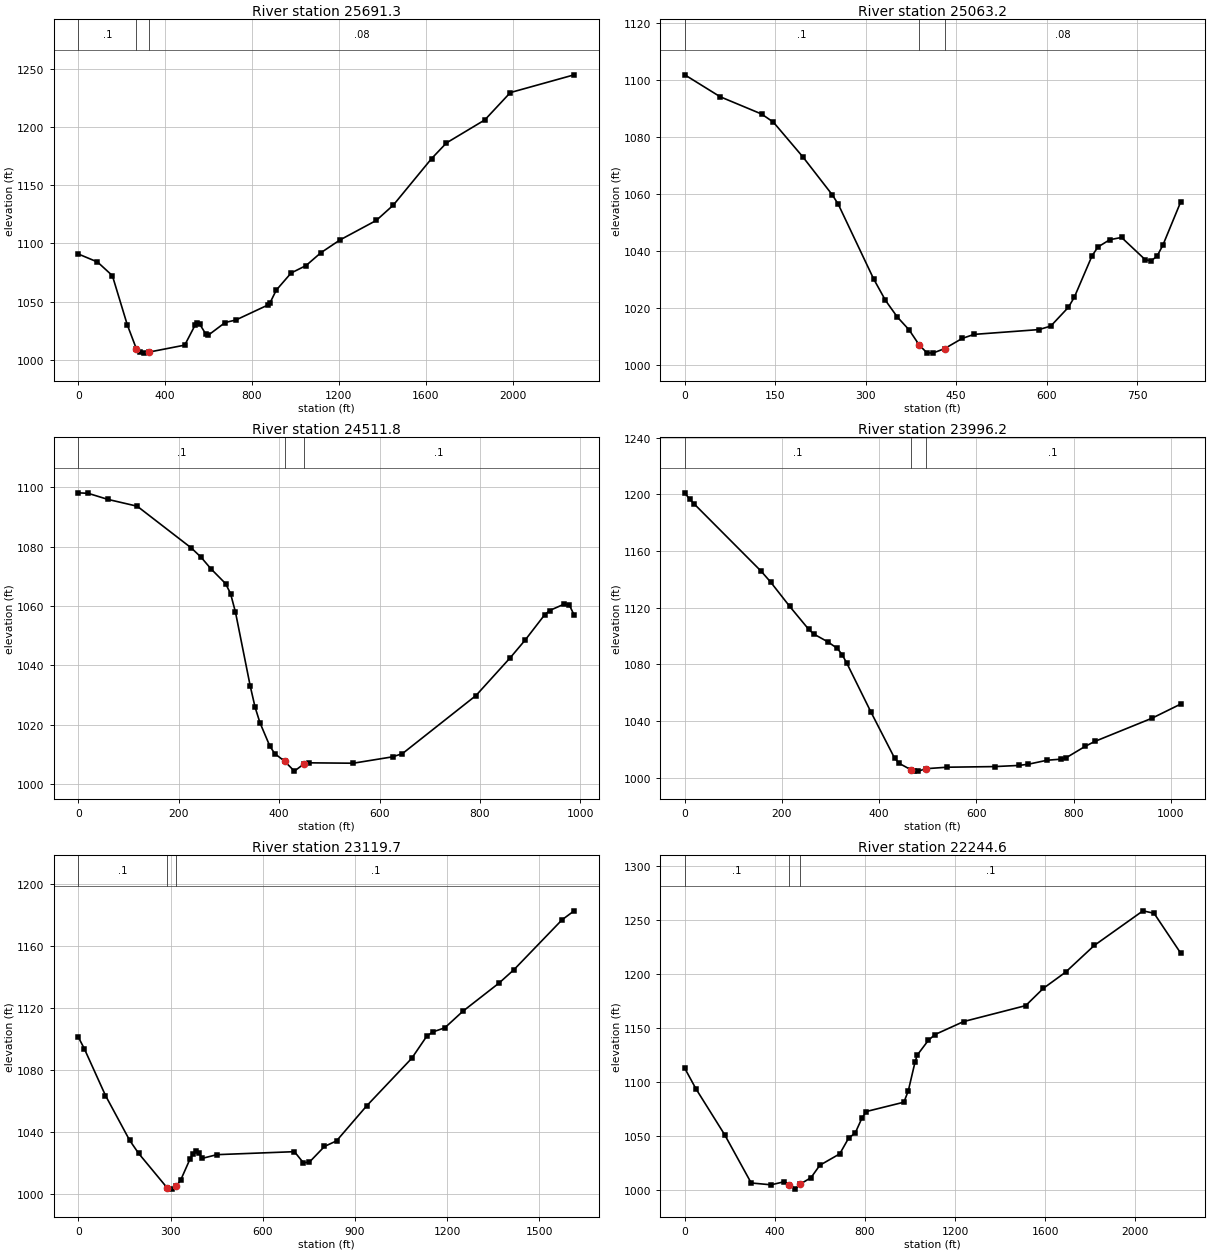
Type RM Length L Ch R = 1 ,25691.3 ,634.3,628,621.5
XS GIS Cut Line= 2
     1789473.632      279037.255     1788500.645      281103.573
#Sta/Elev= 30
       0 1090.92    88.2 1084.06   156.8 1072.33   225.4 1030.12     2671009.625
   284.3 1006.32   303.9 1005.74   323.5 1006.56   490.1 1012.62   539.1 1030.26
   548.9  1031.7   558.7 1030.79   588.1 1021.84   597.9 1021.06   676.4 1032.06
   725.4 1034.19   872.4 1047.01   882.2 1048.66   911.6 1059.84   980.2 1074.61
  1048.8 1080.98  1117.5 1092.06  1205.7 1103.05  1372.3 1119.76  1450.7  1132.9
  1627.2 1172.94  1695.8  1186.4  1872.2 1206.14  1989.9 1229.66  2283.9 1244.91
#Mann= 3 , 0 , 0
       0      .1       0     267    .045       0   323.5     .08       0
Bank Sta=267,323.5
XS Rating Curve= 0 ,0
Exp/Cntr=0.3,0.1

Type RM Length L Ch R = 1 ,25063.2 ,563.7,551.4,539
XS GIS Cut Line= 2
     1788889.989      278641.797     1788683.757      279437.507
#Sta/Elev= 30
       0 1101.93    58.7 1094.21   127.2 1088.15   146.8 1085.29   195.7 1073.07
   244.6 1059.69   254.4 1056.41   313.1 1030.12   332.7 1022.58   352.3 1016.74
   371.9  1012.2   388.81006.839   401.2 1004.18     411 1004.03   430.6  1005.6
   459.9  1009.2   479.5 1010.62   587.1 1012.31   606.7 1013.54   636.1 1020.19
   645.9 1023.76   675.2 1038.28     685 1041.38   704.6 1043.93   724.1 1044.72
   763.3  1036.9   773.1 1036.49   782.9 1038.14   792.6 1042.02     822 1057.16
#Mann= 3 , 0 , 0
       0      .1       0   388.8    .045       0   430.6     .08       0
Bank Sta=388.8,430.6
XS Rating Curve= 0 ,0
Exp/Cntr=0.3,0.1

Type RM Length L Ch R = 1 ,24511.8 ,538,515.6,493.1
XS GIS Cut Line= 2
     1788223.814      278441.714     1788320.379      279424.434
#Sta/Elev= 30
       0 1098.19    19.6 1098.02    58.7 1095.98   117.3 1093.67   224.9  1079.6
   244.4 1076.47     264 1072.57   293.3 1067.55   303.1 1064.21   312.9 1057.95
   342.2  1033.1     352 1025.85   361.7 1020.62   381.3 1012.77   391.1 1010.21
   410.6 1007.67   430.2  1004.3   449.7 1006.78   459.5  1007.1   547.5 1006.97
   625.7 1009.12   645.3 1010.19   791.9 1029.81   860.4 1042.61   889.7 1048.49
   928.8 1057.07   938.6 1058.49   967.9 1060.67   977.7 1060.38   987.4 1056.92
#Mann= 3 , 0 , 0
       0      .1       0   410.6    .045       0   449.7      .1       0
Bank Sta=410.6,449.7
XS Rating Curve= 0 ,0
Exp/Cntr=0.3,0.1

Type RM Length L Ch R = 1 ,23996.2 ,874.8,876.5,877.7
XS GIS Cut Line= 2
     1787488.207      278718.592     1788171.111      279476.777
#Sta/Elev= 30
       0 1201.16     9.8  1196.7    19.6  1193.2     157 1145.84   176.6 1138.15
   215.8 1120.98   255.1 1104.68   264.9 1101.52   294.3 1095.91     314 1091.24
   323.8 1086.84   333.6 1080.71   382.6 1046.63   431.7 1013.79   441.5    1010
   465.81005.494     471 1004.58   480.8 1004.58   495.81006.282   539.6 1007.34
   637.8 1007.79   686.8 1008.59   706.4 1009.42   745.7 1012.28   775.1 1013.06
   784.9 1014.04   824.2 1022.12   843.8 1025.56   961.5 1041.96  1020.4 1051.92
#Mann= 3 , 0 , 0
       0      .1       0   465.8    .045       0   495.8      .1       0
Bank Sta=465.8,495.8
XS Rating Curve= 0 ,0
Exp/Cntr=0.3,0.1

Type RM Length L Ch R = 1 ,23119.7 ,824.2,875.1,925.9
XS GIS Cut Line= 4
     1787396.939      279621.127     1787654.538      279930.553
     1787904.567      279763.772     1788475.888      280472.633
#Sta/Elev= 30
       0 1101.12    19.6 1093.59    88.4 1063.39   166.9 1034.49   196.4 1025.96
   289.31003.699   304.4 1002.92   319.31004.738   333.9 1009.13   363.3  1022.3
   373.2  1025.8     383 1027.44   392.8 1026.08   402.6 1022.77   451.1 1025.19
   703.2 1027.12   732.5 1019.93   752.1 1020.39   801.1  1030.5   840.2 1034.08
   938.1 1056.66    1085 1087.43  1133.9 1101.72  1153.5 1104.47  1192.6 1107.13
  1251.4 1117.83  1368.9 1136.01  1417.8 1144.72  1574.4 1176.96  1613.6 1182.72
#Mann= 3 , 0 , 0
       0      .1       0   289.3    .045       0   319.3      .1       0
Bank Sta=289.3,319.3
XS Rating Curve= 0 ,0
Exp/Cntr=0.3,0.1

Type RM Length L Ch R = 1 ,22244.6 ,660.9,661,657.6
XS GIS Cut Line= 2
     1787133.785      279438.383     1785545.615      280963.895
#Sta/Elev= 30
       0 1112.62    49.2 1093.75     177 1051.16   294.9 1006.44   383.4 1004.73
   442.4 1007.63   464.6 1004.95   491.6 1000.74   511.2 1005.25   560.4 1011.33
   599.7 1022.84   688.2 1033.41   727.5 1047.93     757 1052.77   786.5 1066.39
   806.1 1072.62   973.3 1081.27   992.9 1092.02  1022.4 1118.28  1032.3 1124.89
  1081.4 1138.45  1110.9 1143.87  1238.7 1155.96    1514  1170.7  1592.6 1186.72
  1690.9 1201.62  1818.7 1226.44    2035  1258.5  2084.2 1256.23  2202.2 1219.41
#Mann= 3 , 0 , 0
       0      .1       0   464.6    .045       0   511.2      .1       0
Bank Sta=464.6,511.2
XS Rating Curve= 0 ,0
Exp/Cntr=0.3,0.1

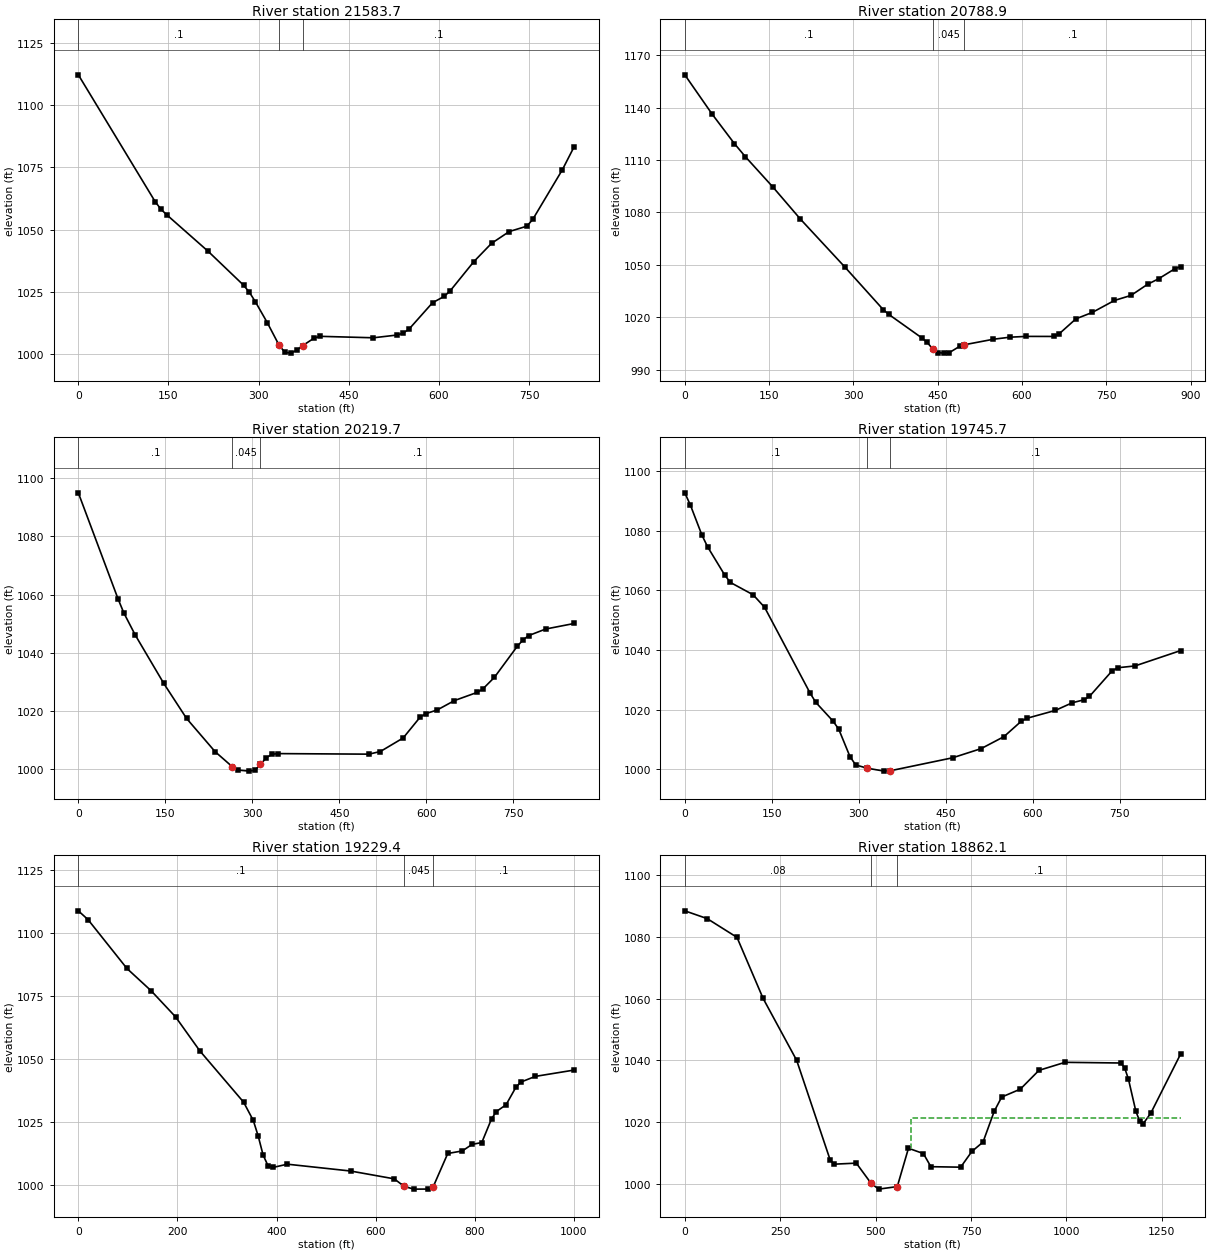
Type RM Length L Ch R = 1 ,21583.7 ,804.7,794.8,784.9
XS GIS Cut Line= 2
     1786684.067      278992.908      1786151.21      279622.805
#Sta/Elev= 30
       0 1112.17   127.7 1061.31   137.5 1058.19   147.3 1055.93   216.1 1041.29
     275 1027.69   284.8 1024.81   294.7 1021.01   314.3 1012.72     334 1003.63
   343.8 1000.74   353.6 1000.44   363.4 1001.61   373.2 1003.45   392.9 1006.56
   402.7 1007.18   491.1  1006.6   530.4 1007.71   540.2 1008.45     550 1010.01
   589.3 1020.66     609 1023.26   618.8 1025.47   658.1 1037.18   687.5 1044.51
     717 1049.25   746.5 1051.42   756.3 1054.21   805.4 1074.07     825 1083.32
#Mann= 3 , 0 , 0
       0      .1       0     334    .045       0   373.2      .1       0
Bank Sta=334,373.2
XS Rating Curve= 0 ,0
Exp/Cntr=0.3,0.1

Type RM Length L Ch R = 1 ,20788.9 ,591.7,569.2,545.4
XS GIS Cut Line= 2
     1786017.584       278351.61     1785656.721      279156.573
#Sta/Elev= 30
       0 1158.74      49 1136.08    88.2 1119.39   107.8 1111.85   156.8 1094.48
   205.8  1076.1   284.2 1048.91   352.9 1024.37   362.7 1021.64   421.5 1008.18
   431.3 1005.52   441.1 1001.82   450.9  999.69   460.7  999.41   470.5  999.67
   490.1 1003.51   497.31004.193   548.9 1007.35   578.3 1008.53   607.7 1008.99
   656.7 1008.96   666.5 1010.57   695.9 1019.03   725.3 1022.75   764.5 1029.57
   793.9 1032.45   823.3 1038.79   842.9 1041.96   872.4  1047.8   882.2 1048.97
#Mann= 3 , 0 , 0
       0      .1       0   441.1    .045       0   497.3      .1       0
Bank Sta=441.1,497.3
XS Rating Curve= 0 ,0
Exp/Cntr=0.3,0.1

Type RM Length L Ch R = 1 ,20219.7 ,472.9,474,476.5
XS GIS Cut Line= 2
     1785218.322      278335.457     1785389.981      279173.112
#Sta/Elev= 30
       0    1095    68.8  1058.4    78.6 1053.69    98.3  1046.1   147.4 1029.51
   186.7 1017.49   235.9 1006.08   265.4 1000.94   275.2  999.77   294.8   999.4
   304.7   999.7   314.11001.686   324.3 1004.03   334.2  1005.2     344 1005.42
   501.2 1005.23   520.9 1006.14   560.2 1010.79   589.7    1018   599.5 1019.15
   619.2 1020.44   648.7 1023.64     688 1026.46   697.8 1027.66   717.5  1031.6
   756.8 1042.22   766.6 1044.42   776.4 1045.94   805.9 1048.21   855.1 1050.12
#Mann= 3 , 0 , 0
       0      .1       0   265.4    .045       0   314.1      .1       0
Bank Sta=265.4,314.1
XS Rating Curve= 0 ,0
Exp/Cntr=0.3,0.1

Type RM Length L Ch R = 1 ,19745.7 ,530.5,516.3,501.3
XS GIS Cut Line= 2
     1784766.933      278432.679     1784938.592      279270.334
#Sta/Elev= 30
       0 1092.77     9.8 1088.58    29.5 1078.59    39.3 1074.64    68.8 1065.18
    78.6 1062.68   117.9 1058.53   137.6 1054.33   216.2 1025.48     226 1022.39
   255.5 1016.15   265.4 1013.44     285 1004.13   294.8  1001.4   314.5  1000.3
     344  999.32   353.8  999.42   461.9  1003.8   511.1 1006.88   550.4  1010.9
   579.9 1016.01   589.7 1017.05   638.8 1019.69   668.3 1022.28     688 1023.25
   697.8 1024.39   737.1 1033.03     747 1034.04   776.4 1034.64   855.1  1039.8
#Mann= 3 , 0 , 0
       0      .1       0   314.5    .045       0   353.8      .1       0
Bank Sta=314.5,353.8
XS Rating Curve= 0 ,0
Exp/Cntr=0.3,0.1

Type RM Length L Ch R = 1 ,19229.4 ,375,367.4,359.8
XS GIS Cut Line= 2
     1784143.093      278583.358     1784709.358       279408.26
#Sta/Elev= 30
       0 1108.78    19.6 1105.28    98.1 1085.89   147.1 1077.01   196.2 1066.69
   245.2 1053.18   333.5 1032.83   353.1 1025.55     363 1019.36   372.8 1011.89
   382.6 1007.66   392.4 1006.89   421.8  1008.2   549.3 1005.49   637.6 1002.38
   657.2  999.42   676.8   998.3   706.3  998.32   716.1  999.22   745.5 1012.45
   774.9 1013.46   794.6 1016.06   814.2 1016.79   833.8 1026.16   843.6  1029.1
   863.2 1031.79   882.8 1038.66   892.7 1040.77   922.1 1043.05  1000.6 1045.57
#Mann= 3 , 0 , 0
       0      .1       0   657.2    .045       0   716.1      .1       0
Bank Sta=657.2,716.1
XS Rating Curve= 0 ,0
Exp/Cntr=0.3,0.1

Type RM Length L Ch R = 1 ,18862.1 ,432.4,438.7,445
XS GIS Cut Line= 2
     1783859.021      279006.902      1784798.65      279904.248
#Sta/Elev= 30
       0 1088.46    58.6 1085.94   136.8 1079.86   205.2 1060.08   293.1 1040.04
     381 1007.73   390.8 1006.38   449.4 1006.72   488.4 1000.14     508   998.3
   556.8  999.12   586.1 1011.54   625.2 1009.82   644.8 1005.57   722.9 1005.41
   752.2  1010.5   781.5 1013.55   810.8 1023.51   830.4 1028.13   879.2 1030.69
   928.1 1036.78   996.4 1039.38    1143 1039.16  1152.8 1037.51  1162.5 1033.96
    1182 1023.51  1191.8 1020.42  1201.6 1019.55  1221.1  1022.9  1299.3 1042.08
#Mann= 3 , 0 , 0
       0     .08       0   488.4    .045       0   556.8      .1       0
#XS Ineff= 2 , 0
                          593.63         1021.29
Permanent Ineff=
       F       F
Bank Sta=488.4,556.8
XS Rating Curve= 0 ,0
Exp/Cntr=0.3,0.1

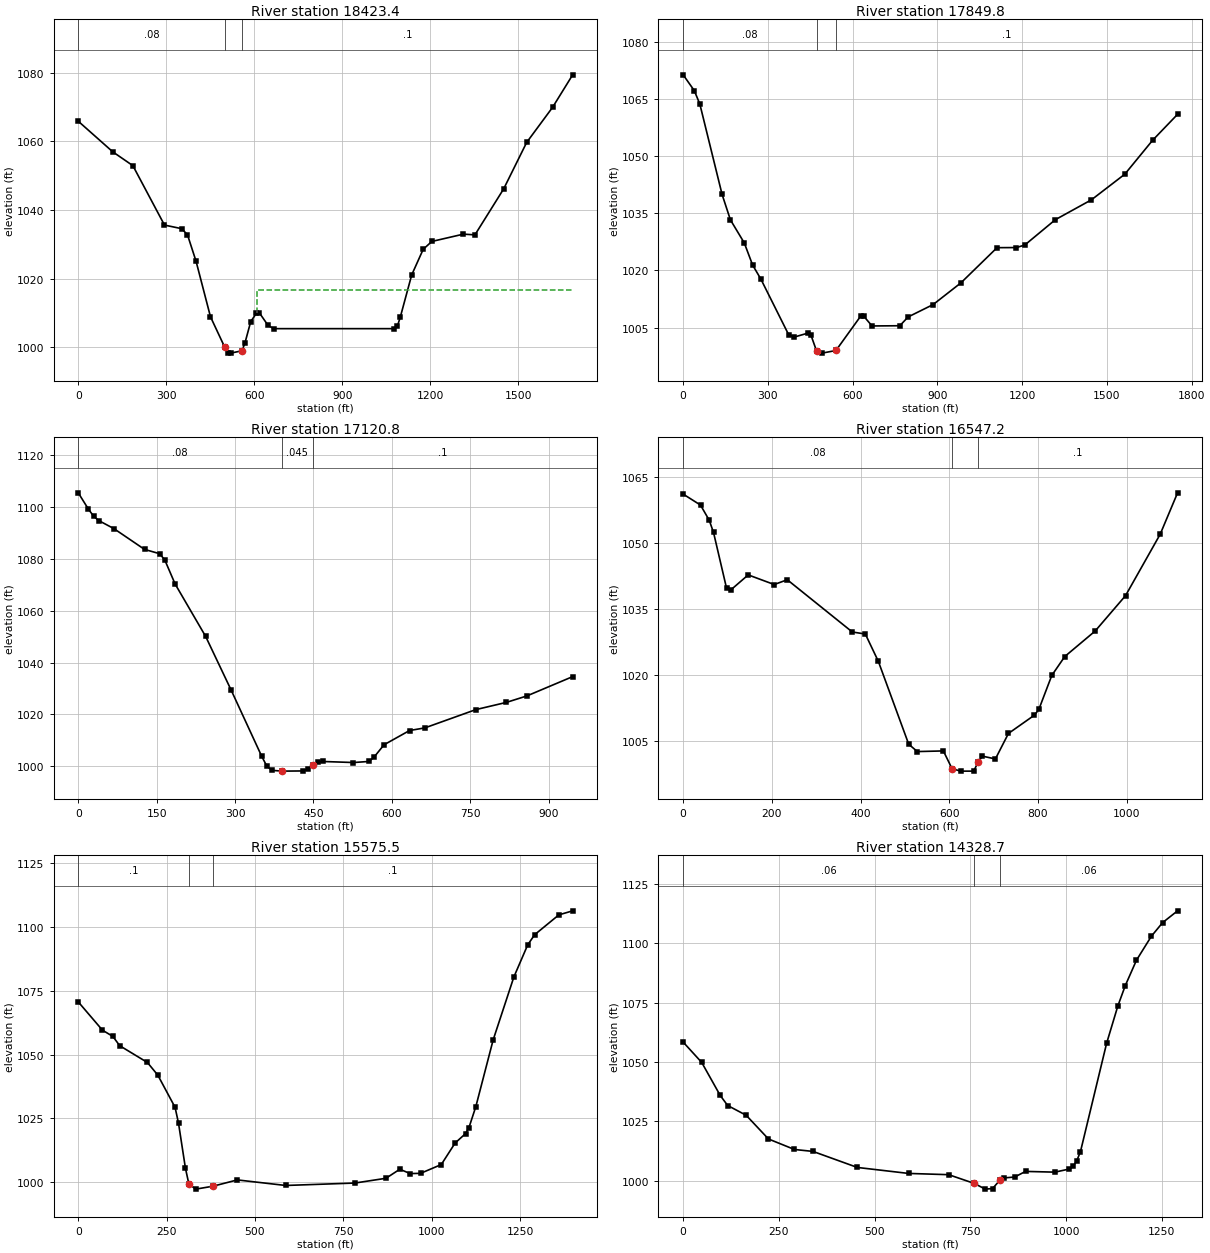
Type RM Length L Ch R = 1 ,18423.4 ,568.5,573.5,578.5
XS GIS Cut Line= 2
     1783572.006      279201.663     1784570.717      280558.295
#Sta/Elev= 30
       0 1065.87   117.5 1056.96   186.1 1052.92   293.8 1035.61   352.6 1034.56
   372.2 1032.77   401.6    1025   450.5 1008.89   499.5  999.94   509.3  998.47
   519.1   998.3   557.8998.9763   568.1  1001.3   587.6 1007.48   607.2 1009.94
     617 1010.05   646.4 1006.41     666 1005.43  1077.4 1005.43  1087.2 1006.15
    1097  1008.7  1136.1 1021.08  1175.3 1028.55  1204.7 1030.84  1312.4 1032.97
  1351.6 1032.76  1449.5 1046.16  1527.9  1059.7    1616  1069.9  1684.6 1079.39
#Mann= 3 , 0 , 0
       0     .08       0   499.5    .045       0   557.8      .1       0
#XS Ineff= 2 , 0
                          609.86         1016.56
Permanent Ineff=
       F       F
Bank Sta=499.5,557.8
XS Rating Curve= 0 ,0
Exp/Cntr=0.3,0.1

Type RM Length L Ch R = 1 ,17849.8 ,724,729.1,733.9
XS GIS Cut Line= 2
     1783189.385      279461.298     1783945.831      281039.575
#Sta/Elev= 30
       0 1071.35    39.3 1067.21      59 1063.68   137.7 1039.97   167.2 1033.29
   216.3 1027.23   245.8 1021.43   275.3  1017.7   373.6 1003.11   393.3 1002.52
   442.5 1003.57   452.3 1003.04     472  998.91   491.6   998.3   540.8  998.99
   629.3  1008.1   639.1 1008.01   668.6 1005.43   766.9 1005.49   796.4  1007.8
   884.9 1011.05   983.2 1016.74  1111.1 1025.98  1179.9 1026.01  1209.4 1026.68
  1317.6 1033.33  1445.4 1038.55  1563.4 1045.27  1661.7 1054.16  1750.2 1060.99
#Mann= 3 , 0 , 0
       0     .08       0     472    .045       0   540.8      .1       0
Bank Sta=472,540.8
XS Rating Curve= 0 ,0
Exp/Cntr=0.3,0.1

Type RM Length L Ch R = 1 ,17120.8 ,573.5,573.6,573.7
XS GIS Cut Line= 2
      1782641.77      279822.239     1782969.101      280709.746
#Sta/Elev= 30
       0 1105.33    19.5 1099.03    29.3 1096.35      39 1094.67    68.3 1091.54
   126.8 1083.55     156 1081.88   165.8 1079.37   185.3 1070.24   243.8 1050.03
   292.6 1029.36   351.1 1003.87   360.8 1000.12   370.6   998.5   390.1   998.2
   429.1  998.27   438.8  998.97   448.6 1000.54   458.3  1001.7   468.1 1001.91
   526.6 1001.51   555.9 1001.92   565.6  1003.5   585.1 1008.35   633.9 1013.83
   663.1 1014.84   760.7 1021.88   819.2 1024.66   858.2 1027.13     946 1034.58
#Mann= 3 , 0 , 0
       0     .08       0   390.1    .045       0   448.6      .1       0
Bank Sta=390.1,448.6
XS Rating Curve= 0 ,0
Exp/Cntr=0.3,0.1

Type RM Length L Ch R = 1 ,16547.2 ,956.4,971.7,986.7
XS GIS Cut Line= 2
     1782083.543       279920.92     1782474.701      280965.252
#Sta/Elev= 30
       0 1061.12    39.1 1058.63    58.7  1055.2    68.5  1052.4    97.8 1039.77
   107.6 1039.37   146.7 1042.77   205.4 1040.58   234.8 1041.67   381.5  1029.8
   410.9 1029.34   440.2 1023.14   508.7 1004.32   528.2 1002.64   586.9 1002.79
   606.5  998.75   626.1   998.2   655.4   998.2   665.2 1000.26     675  1001.6
   704.3 1000.97   733.7 1006.76   792.4 1010.92   802.2  1012.2   831.5 1019.94
   860.8 1024.23   929.3 1030.02   997.8 1038.05    1076 1052.01  1115.2 1061.41
#Mann= 3 , 0 , 0
       0     .08       0   606.5    .045       0   665.2      .1       0
Bank Sta=606.5,665.2
XS Rating Curve= 0 ,0
Exp/Cntr=0.3,0.1

Type RM Length L Ch R = 1 ,15575.5 ,1262.7,1246.9,1231.3
XS GIS Cut Line= 2
     1781705.969       279792.63     1781548.757       281182.57
#Sta/Elev= 30
       0 1070.58    68.5 1059.51    97.8 1057.09   117.4 1053.44   195.6 1046.89
     225 1041.96   273.9 1029.35   283.7 1023.11   303.2 1005.57     313  999.35
   332.6  997.38   381.5  998.53     450 1000.98   586.9  998.81   782.6  999.76
   870.6 1001.62   909.7 1005.15   939.1 1003.46   968.4 1003.55  1027.1 1006.99
  1066.2  1015.4  1095.6 1019.07  1105.4 1021.45  1124.9 1029.68  1173.8  1055.7
  1232.5 1080.34  1271.6 1092.87  1291.2 1096.84  1359.7  1104.6  1398.8 1106.18
#Mann= 3 , 0 , 0
       0      .1       0     313    .045       0   381.5      .1       0
Bank Sta=313,381.5
XS Rating Curve= 0 ,0
Exp/Cntr=0.3,0.1

Type RM Length L Ch R = 1 ,14328.7 ,82,82.2,82
XS GIS Cut Line= 5
     1780918.091       279702.14     1780802.787      280122.356
     1780827.755      280416.971     1780936.348      280703.021
     1780895.558      280953.201
#Sta/Elev= 30
       0 1058.39    48.4 1049.82    96.8 1035.88   116.2 1031.66   164.6 1027.53
   222.7 1017.54   290.5 1013.12   338.9  1012.3   454.8 1005.54   588.4 1003.02
   693.3 1002.49   760.1   998.8   788.8   996.4   807.9  996.65     827 1000.19
   836.6 1001.12   865.3 1001.49     894 1003.87   970.5 1003.56  1008.7 1004.89
  1018.3 1006.01  1027.8 1008.41  1037.4 1012.25  1105.6 1057.88  1134.9  1073.6
  1154.4 1082.23  1183.6 1092.93  1222.6 1103.05  1251.9 1108.78  1290.9 1113.74
#Mann= 3 , 0 , 0
       0     .06       0   760.1    .045       0     827     .06       0
Bank Sta=760.1,827
XS Rating Curve= 0 ,0
Exp/Cntr=0.3,0.1

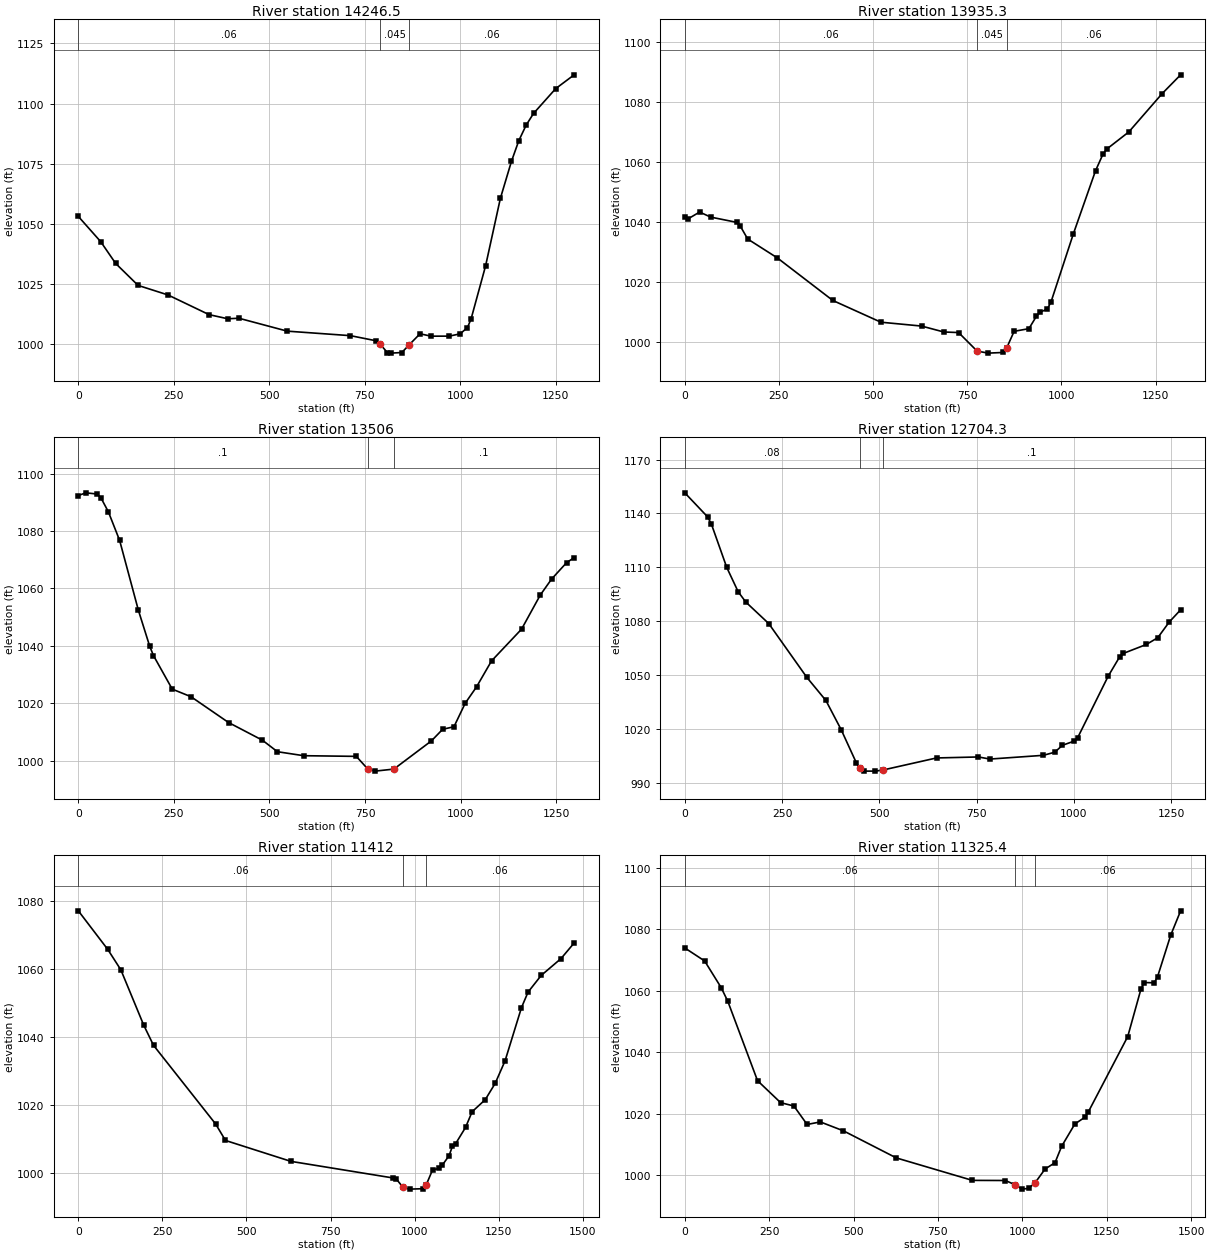
Type RM Length L Ch R = 1 ,14246.5 ,289.6,311.1,332.6
XS GIS Cut Line= 5
     1780840.942      279680.971     1780721.871      280114.921
     1780748.987       280434.89     1780853.935       280711.34
       1780816.6      280940.327
#Sta/Elev= 30
       0 1053.13    58.7 1042.64    97.8 1033.62   156.5 1024.51   234.8 1020.55
   342.4 1012.38   391.3 1010.66   420.6 1010.88   547.3 1005.52   712.7 1003.65
   780.6 1001.51   790.2  1000.2   809.3  996.66   818.8   996.4   847.4  996.65
   866.5  999.83   895.1 1004.43   923.7 1003.44   971.4 1003.45    1000  1004.4
  1019.1 1006.97  1028.6 1010.48  1066.8 1032.62  1105.5 1060.62  1134.5 1075.97
  1153.8 1084.58  1173.1 1091.03  1192.5  1095.9  1250.5 1106.18  1298.8  1111.9
#Mann= 3 , 0 , 0
       0     .06       0   790.2    .045       0   866.5     .06       0
Bank Sta=790.2,866.5
XS Rating Curve= 0 ,0
Exp/Cntr=0.3,0.1

Type RM Length L Ch R = 1 ,13935.3 ,429.8,429.3,428.6
XS GIS Cut Line= 2
     1780664.034      279640.459     1780341.146      280916.747
#Sta/Elev= 30
       0 1041.74     9.8  1041.2    39.3 1043.38    68.8  1041.7   137.5 1039.96
   147.4 1038.69     167  1034.4   245.6 1028.12     393 1013.94   520.7  1006.7
   628.8 1005.41   687.7 1003.44     727 1003.25   776.1  997.08   805.6   996.4
   844.9  996.62   854.7  998.14   874.4 1003.66   913.7 1004.55   933.3 1008.61
   943.2 1010.01   962.8 1011.11   972.6 1013.54  1031.6 1036.09  1090.5 1057.12
  1110.2 1062.63    1120 1064.32    1179 1070.07  1267.4 1082.82  1316.5 1089.08
#Mann= 3 , 0 , 0
       0     .06       0   776.1    .045       0   854.7     .06       0
Bank Sta=776.1,854.7
XS Rating Curve= 0 ,0
Exp/Cntr=0.3,0.1

Type RM Length L Ch R = 1 ,13506   ,813.5,801.7,790.1
XS GIS Cut Line= 2
     1780247.044      279543.665      1779932.64      280802.283
#Sta/Elev= 30
       0 1092.36    19.7  1093.3    49.1 1092.88      59 1091.58    78.6 1086.69
   108.1 1076.71   157.2 1052.37   186.7  1039.9   196.6 1036.63   245.7 1024.95
   294.8 1022.31   393.1 1013.32   481.6 1007.17   520.9 1003.16   589.7 1001.77
   727.3 1001.54   756.8  997.21   776.4   996.4   825.6  997.11   923.8 1006.93
   953.3 1010.97   982.8 1011.85  1012.3 1020.05  1041.8 1025.72  1081.1 1034.77
  1159.7 1045.84  1208.8 1057.74  1238.3 1063.28  1277.6    1069  1297.3 1070.74
#Mann= 3 , 0 , 0
       0      .1       0   756.8    .045       0   825.6      .1       0
Bank Sta=756.8,825.6
XS Rating Curve= 0 ,0
Exp/Cntr=0.3,0.1

Type RM Length L Ch R = 1 ,12704.3 ,1299.7,1292.4,1284.3
XS GIS Cut Line= 2
      1779359.87       279417.05     1779478.992       280686.31
#Sta/Elev= 30
       0 1151.45    58.8 1138.02    68.6 1133.91   107.9 1109.88   137.3 1096.32
   156.9  1090.6   215.7 1078.66   313.8 1048.65   362.8 1035.78   402.1  1019.5
   441.3 1000.94   449.4997.9966   460.9  996.46   490.3  996.44   509.9  997.08
   647.2 1003.78   755.1 1004.33   784.5 1003.16   921.8 1005.24   951.2 1006.98
   970.8 1010.82  1000.3  1013.1  1010.1 1015.06  1088.5  1049.3  1117.9 1060.04
  1127.7 1062.03  1186.6 1066.98    1216 1070.75  1245.4 1079.46  1274.8  1086.3
#Mann= 3 , 0 , 0
       0     .08       0   449.4    .045       0   509.9      .1       0
Bank Sta=449.4,509.9
XS Rating Curve= 0 ,0
Exp/Cntr=0.3,0.1

Type RM Length L Ch R = 1 ,11412   ,86.5,86.5,86.5
XS GIS Cut Line= 4
     1778478.475       279475.41     1778550.051      280113.026
     1778675.432      280505.302       1779056.6      280683.743
#Sta/Elev= 30
       0 1077.16    87.5 1065.82   126.4 1059.83   194.4 1043.58   223.6 1037.64
   408.3 1014.53   437.5  1009.7   631.9 1003.56   935.8  998.68   945.6  998.36
   965.2  995.95   984.8   995.4    1024  995.52  1033.8  996.52  1053.4 1001.08
    1073 1001.47  1082.8 1002.52  1102.4 1005.23  1112.2 1007.96    1122 1008.78
  1151.3 1013.52  1170.9 1018.14    1210 1021.69  1239.4 1026.46  1268.8 1033.08
  1317.7 1048.74  1337.3  1053.3  1376.4 1058.19  1435.2 1063.13  1474.3 1067.72
#Mann= 3 , 0 , 0
       0     .06       0   965.2    .045       0  1033.8     .06       0
Bank Sta=965.2,1033.8
XS Rating Curve= 0 ,0
Exp/Cntr=0.3,0.1

Type RM Length L Ch R = 1 ,11325.4 ,936.1,907.8,879.4
XS GIS Cut Line= 2
     1778270.966      279521.752     1778718.272      280921.225
#Sta/Elev= 30
       0 1073.98    58.8 1069.74   107.7 1061.07   127.3 1056.64   215.5 1030.75
     284 1023.58   323.2  1022.5   362.4 1016.48   401.6 1017.31   470.2  1014.4
   626.9 1005.58   852.2  998.27   950.1  998.23   979.5   996.8   999.1  995.42
  1018.7  995.66  1038.2  997.52  1067.6 1001.98    1097 1004.03  1116.6 1009.37
  1155.8 1016.64  1185.2 1018.81    1195 1020.42  1312.5 1045.12  1351.7  1060.6
  1361.5 1062.71  1390.9 1062.63  1400.7 1064.56  1439.8 1078.13  1469.2 1086.07
#Mann= 3 , 0 , 0
       0     .06       0   979.5    .045       0  1038.2     .06       0
Bank Sta=979.5,1038.2
XS Rating Curve= 0 ,0
Exp/Cntr=0.3,0.1