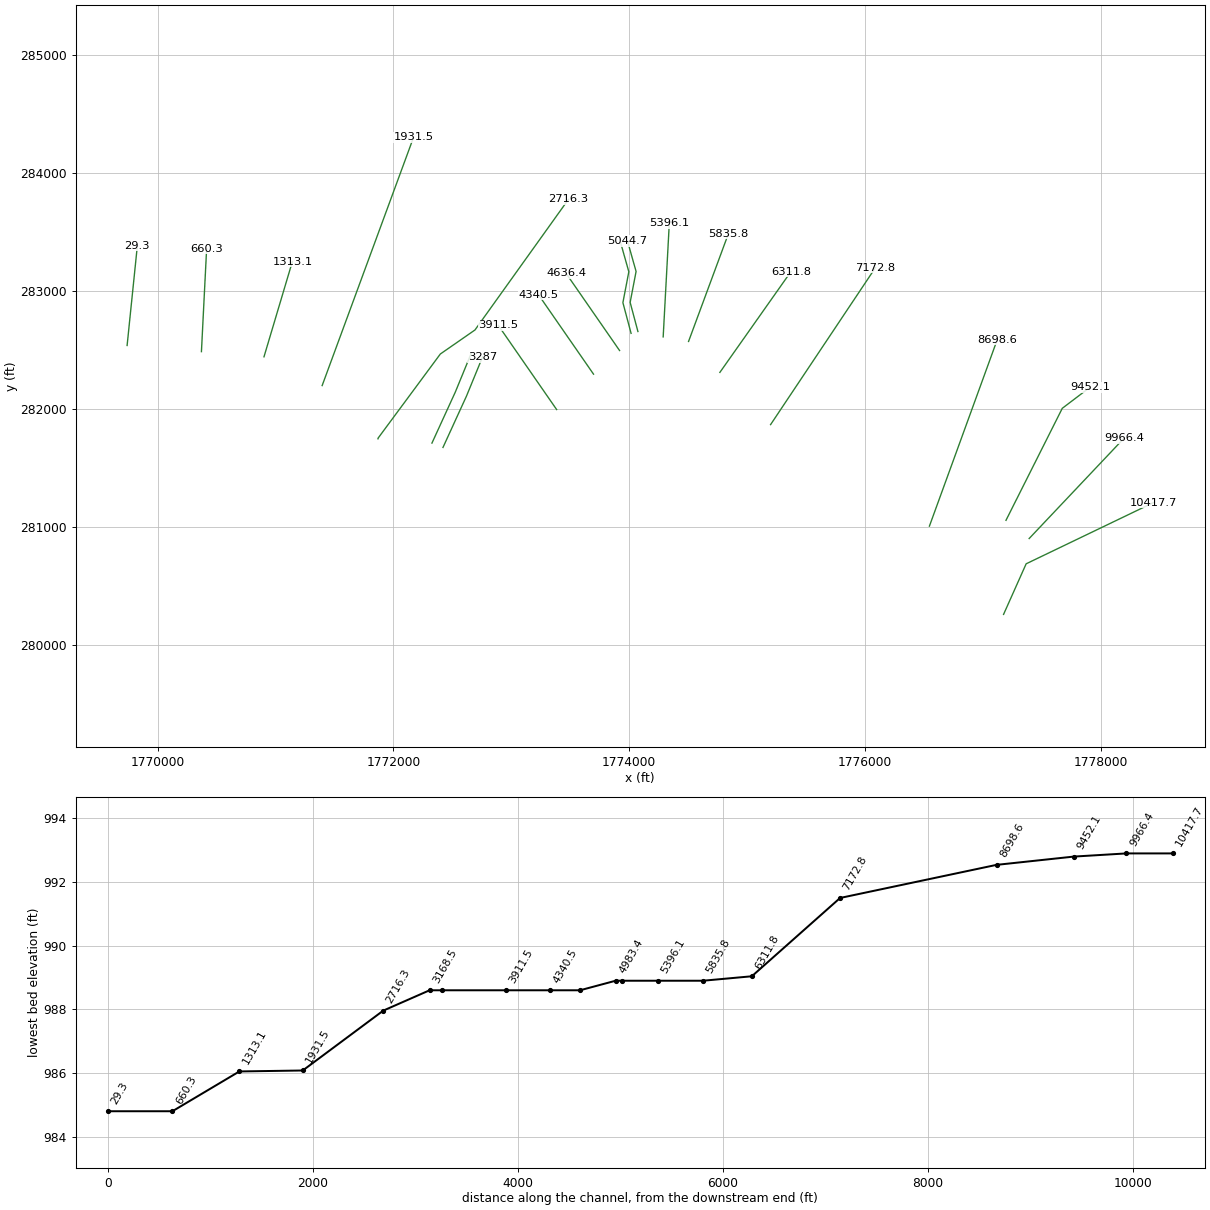
HEC-RAS study SimpsonCrk.prj: SimpsonCrk

--- SimpsonCrk.g01 (geometry) --- (continued)

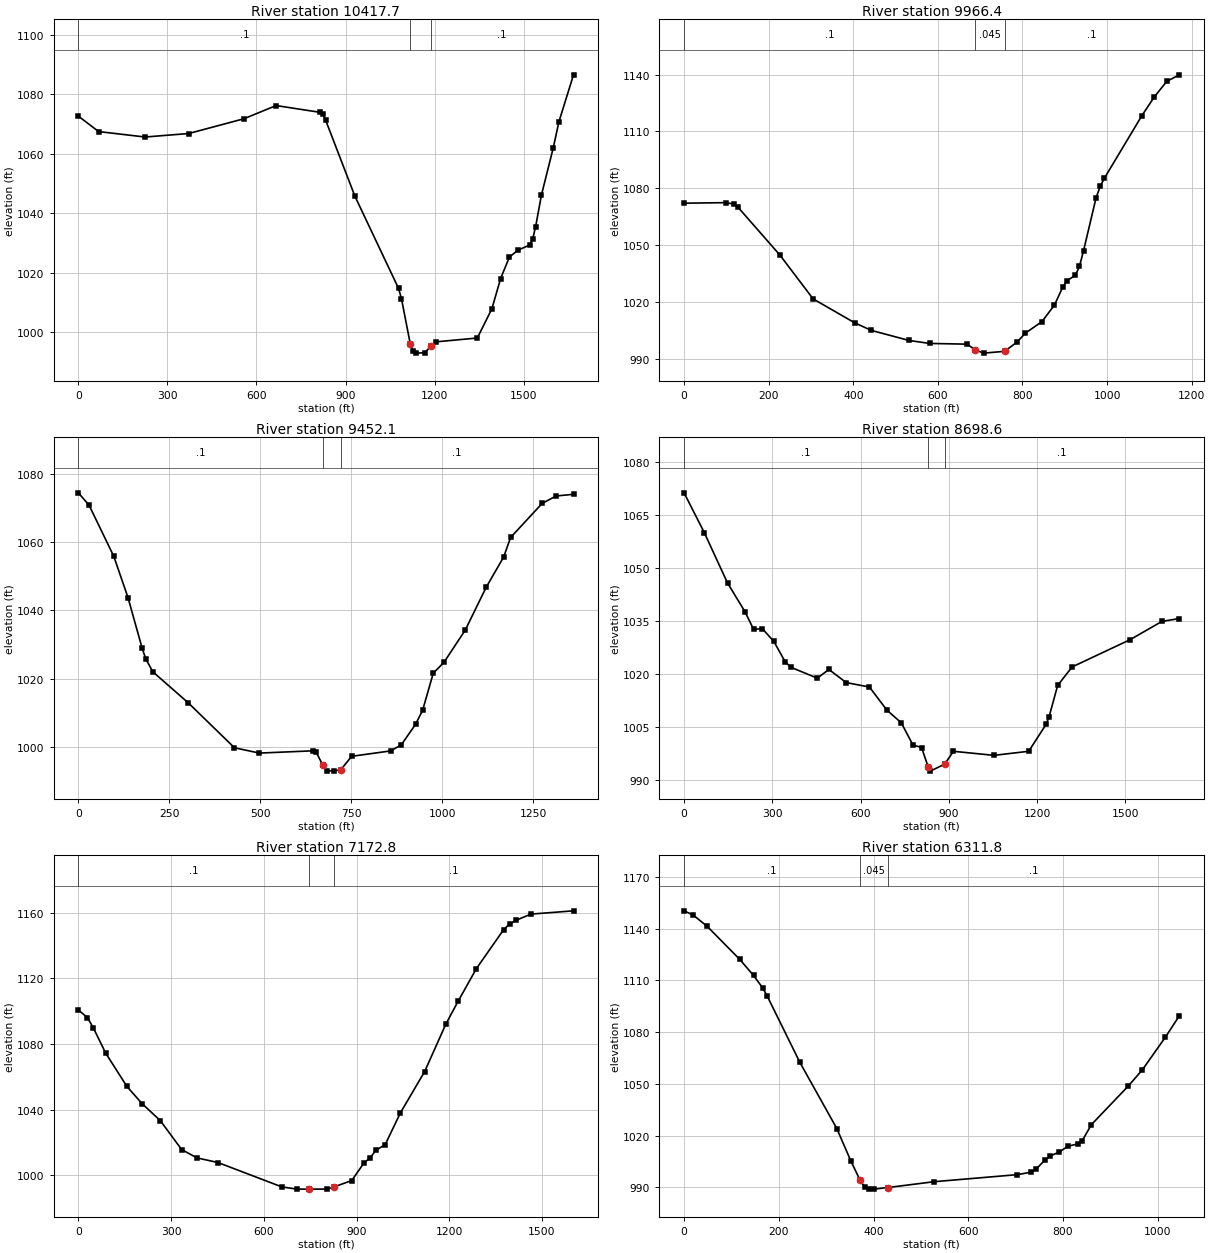
Type RM Length L Ch R = 1 ,10417.7 ,437.3,451.3,465.2
XS GIS Cut Line= 3
     1777176.933      280260.335     1777368.601      280689.226
     1778448.279      281207.944
#Sta/Elev= 30
       0  1072.6    68.5 1067.39   225.1 1065.56   371.9 1066.74   558.1 1071.71
   666.1 1076.14   813.4 1073.87   823.2 1073.14     833  1071.2   931.2 1045.72
  1078.5 1014.65  1088.3 1011.18  1117.8  996.05  1127.6  993.55  1137.4   992.9
  1166.9  993.02  1186.5  995.17  1206.1  996.71  1343.6  997.98  1392.7 1007.81
  1422.1 1017.95  1451.6 1025.19    1481 1027.55  1520.3 1029.26  1530.1  1031.3
    1540 1035.42  1559.6 1046.06  1598.9 1061.72  1618.5 1070.71  1667.6 1086.47
#Mann= 3 , 0 , 0
       0      .1       0  1117.8    .045       0  1186.5      .1       0
Bank Sta=1117.8,1186.5
XS Rating Curve= 0 ,0
Exp/Cntr=0.3,0.1

Type RM Length L Ch R = 1 ,9966.4  ,506.4,514.3,521.3
XS GIS Cut Line= 2
     1777394.151      280903.648     1778199.029      281753.771
#Sta/Elev= 30
       0 1072.11    98.4  1072.4     118 1071.65   127.9 1069.86   226.3 1044.76
     305 1021.56   403.4 1008.89   442.7 1004.91   531.2  999.62   580.4  998.02
     669  997.64   688.6   994.6   708.3   992.9   757.5  993.85     787   998.7
   806.7 1003.45     846 1009.56   875.6  1018.3   895.2 1027.79   905.1 1031.24
   924.8 1033.92   934.6 1038.68   944.4 1047.06   973.9 1074.94   983.8 1081.05
   993.6 1085.32  1082.2 1118.35  1111.7 1128.31  1141.2 1136.48  1170.7 1139.93
#Mann= 3 , 0 , 0
       0      .1       0   688.6    .045       0   757.5      .1       0
Bank Sta=688.6,757.5
XS Rating Curve= 0 ,0
Exp/Cntr=0.3,0.1

Type RM Length L Ch R = 1 ,9452.1  ,745.4,753.6,761.4
XS GIS Cut Line= 3
     1777197.421      281057.792      1777675.14      282007.448
     1777912.219      282187.182
#Sta/Elev= 30
       0 1074.55    29.3 1070.98    97.5  1055.9   136.5 1043.79   175.6 1028.83
   185.3 1025.79   204.8 1021.98   302.3 1012.84   429.1  999.66   497.4   998.1
   643.7  998.76   653.4  998.39   672.2994.4805   682.7  992.97   702.2   992.8
   721.7  993.26     751  997.15   858.2  998.74   887.5 1000.53   926.5 1006.53
     946 1010.66   975.3  1021.6  1004.5 1024.73    1063  1034.2  1120.6  1046.8
  1168.6 1055.68  1187.8 1061.44  1274.2 1071.42  1312.6 1073.62  1360.6 1074.12
#Mann= 3 , 0 , 0
       0      .1       0   672.2    .045       0   721.7      .1       0
Bank Sta=672.2,721.7
XS Rating Curve= 0 ,0
Exp/Cntr=0.3,0.1

Type RM Length L Ch R = 1 ,8698.6  ,1533.3,1525.8,1518.8
XS GIS Cut Line= 2
     1776547.824      281008.674     1777123.508      282590.012
#Sta/Elev= 30
       0 1071.39    68.9 1060.07   147.6 1045.85   206.7 1037.74   236.2  1032.7
   265.7 1032.91   305.1 1029.28   344.4 1023.39   364.1 1021.92   452.7 1018.88
   492.1 1021.34   551.1 1017.62   629.8 1016.37   688.9 1009.85   738.1 1006.23
   777.5  999.96     807  999.23   829.8993.6475   836.5  992.54   885.7  994.52
   915.2  998.16    1053  997.01  1171.1  998.16  1230.2 1005.79    1240 1007.83
  1269.5 1016.82  1318.7 1022.06  1515.6 1029.78  1623.8 1034.96  1682.9 1035.77
#Mann= 3 , 0 , 0
       0      .1       0   829.8    .045       0   885.7      .1       0
Bank Sta=829.8,885.7
XS Rating Curve= 0 ,0
Exp/Cntr=0.3,0.1

Type RM Length L Ch R = 1 ,7172.8  ,865.9,860.9,855.5
XS GIS Cut Line= 2
     1775200.031      281869.226      1776090.45      283201.032
#Sta/Elev= 30
       0 1100.74    29.5 1096.14    49.1 1089.63    88.5 1074.45   157.3 1054.08
   206.4 1043.62   265.4 1033.24   334.2 1015.66   383.3 1010.58   452.1  1007.7
   658.5  992.85   707.6   991.5     747   991.5   805.9  991.51   825.6  992.74
   884.6  996.73   923.9 1007.41   943.5  1010.5   963.2 1015.28   992.7 1018.59
  1041.8 1037.94  1120.4 1063.16  1189.2 1092.21  1228.6 1106.03  1287.5 1125.86
    1376 1149.72  1395.6  1153.2  1415.3 1155.34  1464.4 1159.18    1602 1161.18
#Mann= 3 , 0 , 0
       0      .1       0     747    .045       0   825.6      .1       0
Bank Sta=747,825.6
XS Rating Curve= 0 ,0
Exp/Cntr=0.3,0.1

Type RM Length L Ch R = 1 ,6311.8  ,466.2,476.1,485.8
XS GIS Cut Line= 2
     1774769.821      282312.039       1775372.7      283166.393
#Sta/Elev= 30
       0 1150.29    19.5 1147.78    48.9 1141.25   117.3 1122.22   146.6 1112.84
   166.1 1105.59   175.9 1100.68   244.3 1062.55   322.5 1024.13   351.8 1005.54
   371.4  994.29   381.1  990.31   390.9  989.08   400.7  989.04     430  989.96
   527.7  993.33   703.6  997.43   732.9  998.87   742.7  1000.5   762.2 1005.96
     772  1008.1   791.6  1010.5   811.1 1013.95   830.7 1015.19   840.4    1017
     860  1026.4   938.2 1048.86   967.5 1058.13  1016.3  1077.1  1045.6 1089.45
#Mann= 3 , 0 , 0
       0      .1       0   371.4    .045       0     430      .1       0
Bank Sta=371.4,430
XS Rating Curve= 0 ,0
Exp/Cntr=0.3,0.1

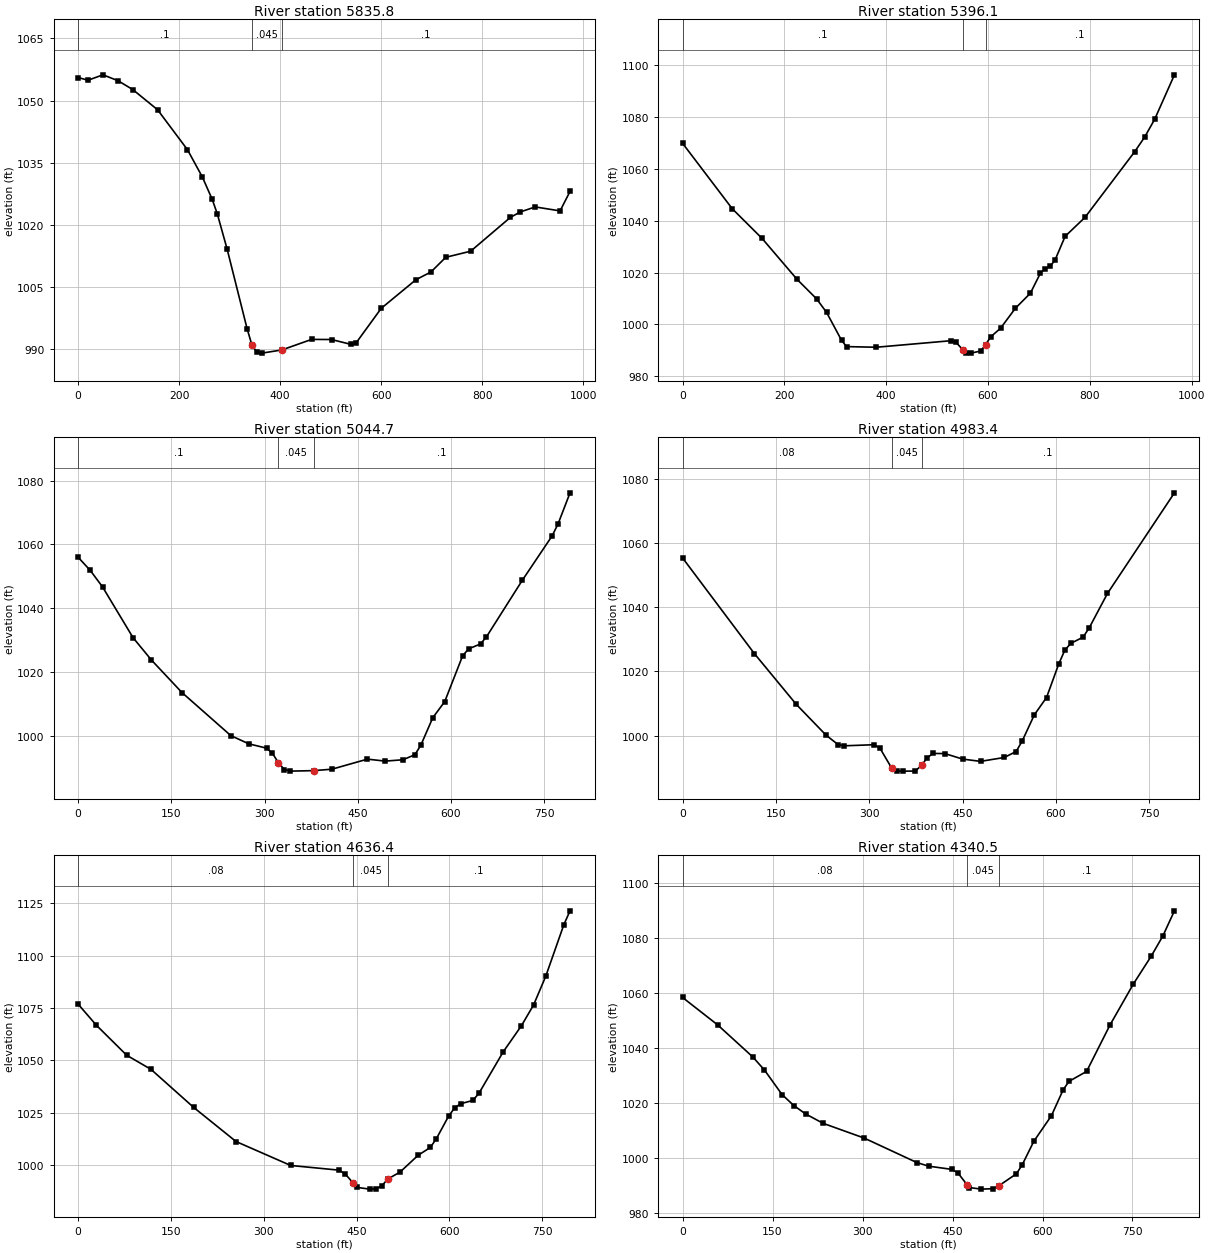
Type RM Length L Ch R = 1 ,5835.8  ,430.1,439.7,449.8
XS GIS Cut Line= 2
     1774503.947      282574.104     1774842.037      283487.611
#Sta/Elev= 30
       0 1055.55    19.7 1054.91    49.2 1056.21    78.7  1054.8   108.2 1052.65
   157.4 1047.75   216.5  1038.1     246  1031.5   265.6 1026.06   275.5 1022.62
   295.2 1013.99   334.5  994.85   344.4  990.75   354.2  989.11     364   988.9
   403.4  989.67   462.4  992.22   501.8  992.19   541.2  990.99     551  991.46
   600.2  999.73     669 1006.66   698.6 1008.52   728.1 1012.08   777.3 1013.55
     856 1021.73   875.7 1023.05   905.2 1024.26   954.4  1023.3   974.1    1028
#Mann= 3 , 0 , 0
       0      .1       0   344.4    .045       0   403.4      .1       0
Bank Sta=344.4,403.4
XS Rating Curve= 0 ,0
Exp/Cntr=0.3,0.1

Type RM Length L Ch R = 1 ,5396.1  ,355.6,351.4,344.6
XS GIS Cut Line= 2
     1774288.662      282612.946     1774340.666        283577.8
#Sta/Elev= 30
       0 1069.92    97.6 1044.65   156.2 1033.18   224.5 1017.47   263.5 1009.81
     283 1004.59   312.3  993.85   322.1  991.42   380.6  991.17     527  993.69
   536.8  993.14   551.1990.0918   556.3   989.1   566.1   988.9   585.6   989.7
   595.4   992.2   605.1  995.15   624.6   998.5   653.9 1006.24   683.2 1012.02
   702.7 1019.67   712.5 1021.54   722.2 1022.38     732 1024.99   751.5 1033.98
   790.6 1041.32   888.2 1066.67   907.7  1072.3   927.2 1079.09   966.2 1096.33
#Mann= 3 , 0 , 0
       0      .1       0   551.1    .045       0   595.4      .1       0
Bank Sta=551.1,595.4
XS Rating Curve= 0 ,0
Exp/Cntr=0.3,0.1

Type RM Length L Ch R = 1 ,5044.7  ,61.5,61.3,62.9
XS GIS Cut Line= 4
     1774074.299      282658.499     1774008.366      282905.326
     1774058.756      283167.704     1773985.642      283426.281
#Sta/Elev= 30
       0 1055.96    19.6 1051.81    39.3 1046.65    88.4 1030.73   117.9 1023.74
     167 1013.55   245.7 1000.03   274.6  997.46   303.2   996.1   312.7  994.46
   322.3  991.52   331.8   989.4   341.4   988.9   379.5  989.06   408.2   989.5
   465.4  992.66     494  992.04   522.6  992.46   541.8  994.05   551.4  997.04
   570.6 1005.65   589.8 1010.69   618.6 1025.06   628.2 1027.23   647.4 1028.78
     657 1031.02   714.6 1048.73   762.6 1062.66   772.2 1066.44   791.4 1076.16
#Mann= 3 , 0 , 0
       0      .1       0   322.3    .045       0   379.5      .1       0
Bank Sta=322.3,379.5
XS Rating Curve= 0 ,0
Exp/Cntr=0.3,0.1

Type RM Length L Ch R = 1 ,4983.4  ,318.9,347.1,374.8
XS GIS Cut Line= 4
     1774016.331      282643.015     1773946.848      282903.132
     1773997.152      283165.059     1773927.905      283409.955
#Sta/Elev= 30
       0 1055.37   115.4 1025.54   182.7 1009.72   230.8 1000.07     250  997.17
   259.6  996.79   307.3  997.13   316.9  996.16   335.9  989.89   345.4  988.91
     355   988.9     374  988.91   384.2990.7255   393.1  993.09   402.6  994.42
   421.6  994.36   450.2  992.65   478.8  991.94   516.9  993.15     536  995.01
   545.7  998.25   565.3 1006.46   584.9 1011.85   604.5  1022.3   614.3 1026.62
     624 1028.74   643.6 1030.66   653.4 1033.54   682.8 1044.29   790.4 1075.65
#Mann= 3 , 0 , 0
       0     .08       0   335.9    .045       0   384.2      .1       0
Bank Sta=335.9,384.2
XS Rating Curve= 0 ,0
Exp/Cntr=0.3,0.1

Type RM Length L Ch R = 1 ,4636.4  ,295.9,295.9,295.9
XS GIS Cut Line= 2
     1773918.464      282497.516     1773465.425      283150.743
#Sta/Elev= 30
       0 1076.84    29.4 1066.82    78.5 1052.47   117.8 1045.73   186.5 1027.64
   255.2 1011.31   343.5  999.89     422  997.64   431.8  995.78   444.6991.4847
   451.4  989.41   471.1   988.6   480.9  988.69   490.7  990.13   500.5  993.44
   520.2  996.72   549.6 1004.77   569.2 1008.48     579 1012.67   598.7 1023.38
   608.5 1027.37   618.3 1029.34   637.9 1030.92   647.7 1034.28     687 1054.09
   716.4 1066.53   736.1 1076.47   755.7 1090.11   785.1 1114.83     795 1121.38
#Mann= 3 , 0 , 0
       0     .08       0   444.6    .045       0   500.5      .1       0
Bank Sta=444.6,500.5
XS Rating Curve= 0 ,0
Exp/Cntr=0.3,0.1

Type RM Length L Ch R = 1 ,4340.5  ,429,428.9,428.8
XS GIS Cut Line= 2
     1773697.677       282296.93     1773230.412      282970.668
#Sta/Elev= 30
       0 1058.45    58.6 1048.44   117.1 1036.77   136.6 1031.99   165.9 1023.05
   185.5 1019.06     205 1016.02   234.3 1012.58   302.6 1007.22   390.4   998.3
     410  996.98     449  995.79   458.8  994.54   474.9  990.02   478.3  989.17
   497.8   988.6   517.3  988.76   527.1   989.8   556.4  994.17   566.1  997.43
   585.6 1006.06   614.9 1015.37   634.5 1024.84   644.2 1027.88   673.5  1031.5
   712.6 1048.46   751.6 1063.42   780.9  1073.4   800.4 1080.78   819.9 1090.03
#Mann= 3 , 0 , 0
       0     .08       0   474.9    .045       0   527.1      .1       0
Bank Sta=474.9,527.1
XS Rating Curve= 0 ,0
Exp/Cntr=0.3,0.1

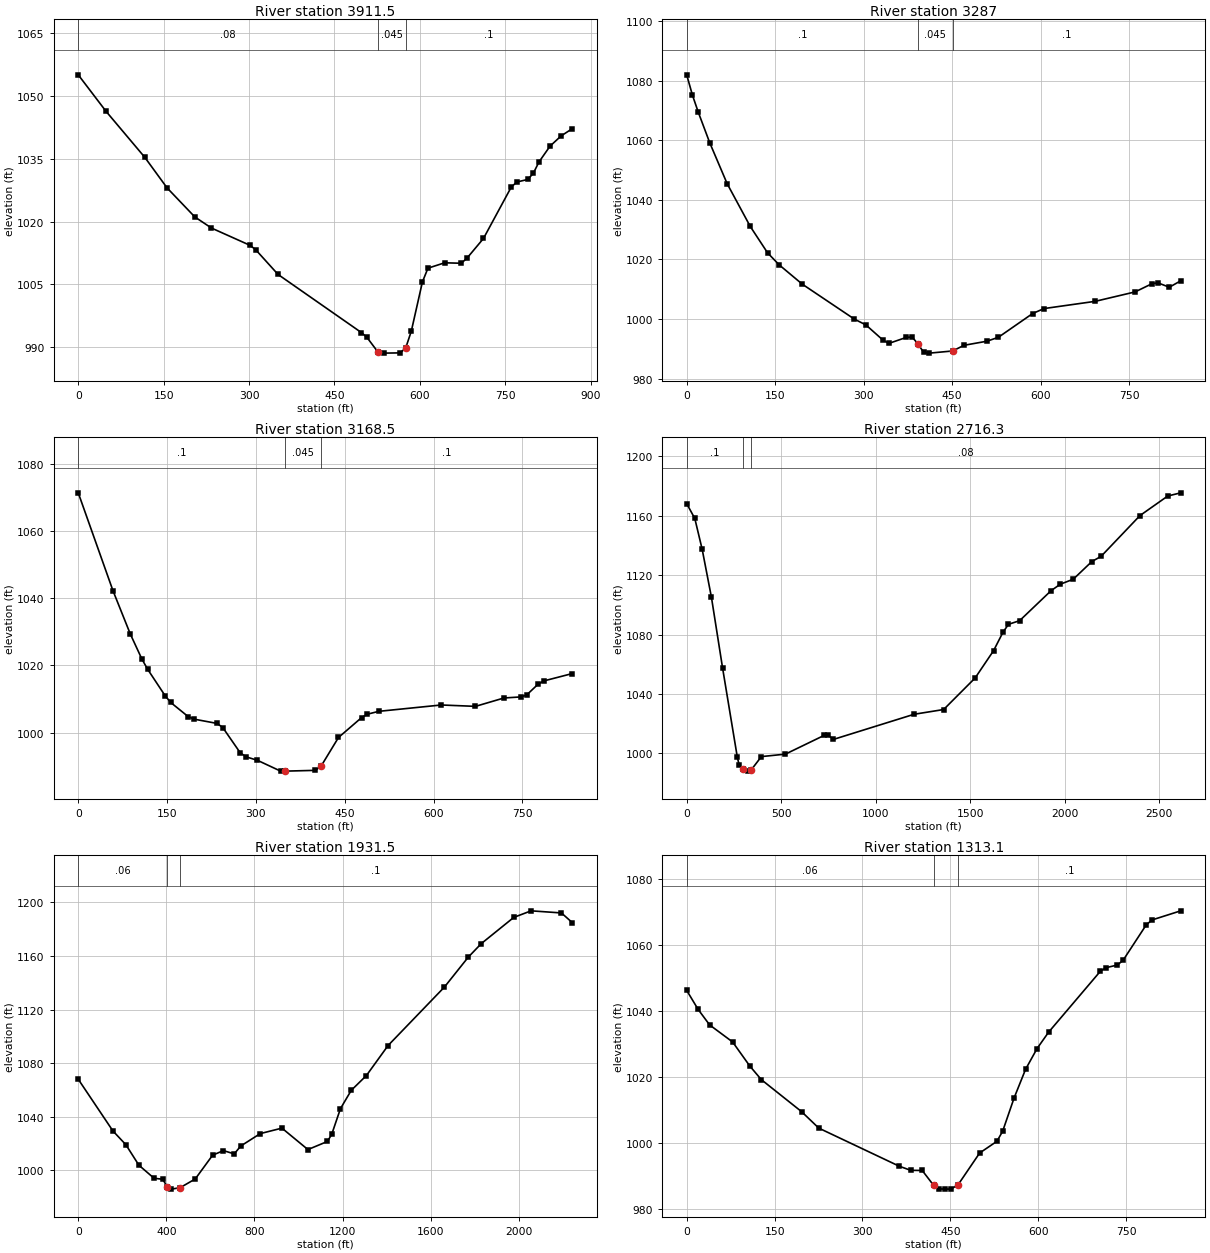
Type RM Length L Ch R = 1 ,3911.5  ,664.1,624.5,581.8
XS GIS Cut Line= 2
     1773384.645      281996.941     1772890.147      282709.946
#Sta/Elev= 30
       0 1055.02    48.8 1046.31     117 1035.31     156 1028.04   204.7 1021.11
     234 1018.45   302.2  1014.3     312 1013.23     351 1007.37   497.2  993.52
     507  992.37   526.5  988.84   536.2   988.6   565.5  988.66   575.2  989.86
     585  993.85   604.5  1005.6   614.2 1008.87   643.5 1010.16   672.7 1010.05
   682.5 1011.22   711.7 1015.96   760.5 1028.22   770.2 1029.43   789.7 1030.06
   799.4 1031.56   809.2 1034.22   828.7 1038.01   848.2 1040.45   867.7 1042.17
#Mann= 3 , 0 , 0
       0     .08       0   526.5    .045       0   575.2      .1       0
Bank Sta=526.5,575.2
XS Rating Curve= 0 ,0
Exp/Cntr=0.3,0.1

Type RM Length L Ch R = 1 ,3287    ,118.4,118.4,123.4
XS GIS Cut Line= 3
     1772420.222      281675.762     1772620.208      282112.255
      1772755.93      282442.858
#Sta/Elev= 30
       0 1081.92     9.8 1075.09    19.6 1069.42    39.2 1059.08    68.6 1045.42
   107.8 1031.07   137.2 1022.21   156.8  1018.2     196 1011.72   284.2 1000.01
   303.8  998.06   333.2  992.89     343  991.88   372.3  993.87   382.1  993.99
   391.9  991.76   401.7  988.84   411.5   988.6   450.7  989.32   470.3  991.23
   509.1   992.6   528.4  993.91   586.4 1001.87   605.7 1003.54   692.6 1005.97
   760.2 1009.13   789.2 1011.92   798.9 1012.16   818.2  1010.7   837.5 1012.85
#Mann= 3 , 0 , 0
       0      .1       0   391.9    .045       0   450.7      .1       0
Bank Sta=391.9,450.7
XS Rating Curve= 0 ,0
Exp/Cntr=0.3,0.1

Type RM Length L Ch R = 1 ,3168.5  ,456.4,452.2,446.3
XS GIS Cut Line= 3
     1772326.659      281712.557     1772525.977      282147.592
      1772661.09      282476.712
#Sta/Elev= 30
       0 1071.32    58.6 1042.25    87.9 1029.36   107.4 1021.94   117.2 1018.87
   146.5 1011.07   156.2    1009   185.6 1004.81   195.3 1004.06   234.4 1002.78
   244.1 1001.55   273.4  994.09   283.2  992.86   302.7  991.81   341.8   988.6
   349.8   988.6   400.4  988.83   410.2  990.11   439.5   998.6   478.5 1004.51
   488.1 1005.51   507.4 1006.37   613.1 1008.26   670.8 1007.85   718.9 1010.34
   747.8 1010.66   757.4 1011.26   776.6 1014.45   786.2 1015.41   834.3  1017.6
#Mann= 3 , 0 , 0
       0      .1       0   349.8    .045       0   410.2      .1       0
Bank Sta=349.8,410.2
XS Rating Curve= 0 ,0
Exp/Cntr=0.3,0.1

Type RM Length L Ch R = 1 ,2716.3  ,774.5,784.9,796.5
XS GIS Cut Line= 5
     1771869.038      281749.042     1771868.419        281752.9
     1772397.847      282467.901     1772691.894      282671.758
     1773484.806      283778.658
#Sta/Elev= 30
       0 1168.23      43  1158.2    82.1 1137.33     131 1105.05   189.7 1057.59
   267.9  997.31   277.6  992.05   297.2  989.16   326.5  987.96   341.1988.7533
     395  997.75   522.1  999.41   727.4 1012.07   746.9 1012.36   776.3 1009.34
    1203 1026.28  1359.1 1029.47  1525.7 1050.74  1623.6 1069.23  1672.6 1081.48
    1702  1086.9  1760.8 1089.33  1927.3 1109.56  1976.3 1113.93  2044.8 1117.29
  2142.8 1129.18  2191.8 1132.68  2397.5 1160.17  2544.4 1173.35    2613  1175.5
#Mann= 3 , 0 , 0
       0      .1       0   297.2    .045       0   341.1     .08       0
Bank Sta=297.2,341.1
XS Rating Curve= 0 ,0
Exp/Cntr=0.3,0.1

Type RM Length L Ch R = 1 ,1931.5  ,616.7,618.4,618.7
XS GIS Cut Line= 2
     1771394.998      282200.227     1772170.577      284304.905
#Sta/Elev= 30
       0 1068.05   157.4 1029.49   216.4 1019.18   275.5  1003.9   344.3  994.18
   383.7  993.45   405.2987.4861     423  986.08   462.4  987.15   531.2  993.65
     610 1011.38   659.1 1014.81   708.3 1012.38   737.8 1018.24   826.4  1027.5
   924.8 1031.58  1042.8 1015.59  1131.4 1021.65    1151 1027.04  1190.4 1046.09
  1239.6 1059.79  1308.4 1070.83  1406.8 1093.22  1662.6 1136.83  1770.8 1159.13
  1829.8 1169.21  1977.4 1188.78  2056.1 1193.68  2193.8  1192.1    2243 1184.89
#Mann= 3 , 0 , 0
       0     .06       0   405.2    .045       0   462.4      .1       0
Bank Sta=405.2,462.4
XS Rating Curve= 0 ,0
Exp/Cntr=0.3,0.1

Type RM Length L Ch R = 1 ,1313.1  ,644,652.8,661.1
XS GIS Cut Line= 2
     1770901.382      282443.906     1771142.359       283251.68
#Sta/Elev= 30
       0 1046.21    19.6 1040.43    39.2 1035.75    78.4 1030.59   107.8 1023.29
   127.4 1019.19     196 1009.51   225.4 1004.52   362.7  992.99   382.3  991.74
   401.9   991.7   421.5  987.17   431.3  986.13   441.1  986.05   450.9  986.08
   462.9987.3167   499.9  996.98   529.3 1000.52   539.1 1003.54   558.7 1013.65
   578.3 1022.33   597.9 1028.61   617.5 1033.54   705.7 1051.96   715.5 1053.08
   735.1 1053.89   744.9 1055.38   784.1 1066.02   793.9 1067.52     843 1070.29
#Mann= 3 , 0 , 0
       0     .06       0   421.5    .045       0   462.9      .1       0
Bank Sta=421.5,462.9
XS Rating Curve= 0 ,0
Exp/Cntr=0.3,0.1

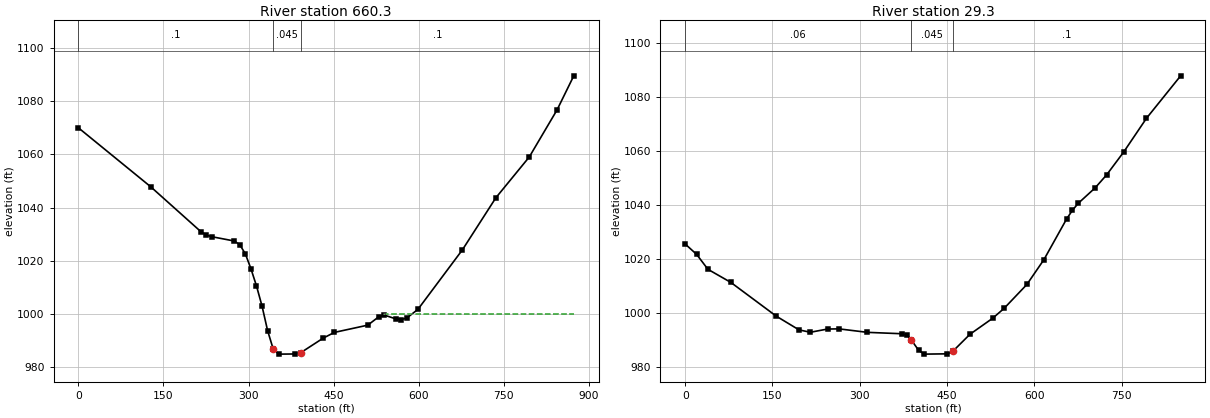
Type RM Length L Ch R = 1 ,660.3   ,632.9,630.9,628.7
XS GIS Cut Line= 2
     1770370.681      282487.849     1770414.716      283359.774
#Sta/Elev= 30
       0 1070.07   127.5 1047.85   215.8 1030.96   225.6 1029.63   235.4 1029.02
   274.7 1027.41   284.5 1026.02   294.3 1022.57   304.1    1017   313.9 1010.52
   323.7 1002.91   333.5  993.68   343.3  986.78   353.1   984.8   382.6  984.86
   392.4  985.41   431.6  990.84   451.2  992.98   510.1  995.72   529.7  998.92
   539.5  999.48   559.1   998.1     569  997.83   578.8   998.4   598.4 1001.66
   676.8 1024.09   735.7 1043.68   794.6 1059.06   843.6 1076.81     873 1089.62
#Mann= 3 , 0 , 0
       0      .1       0   343.3    .045       0   392.4      .1       0
#XS Ineff= 2 , 0
                          539.01            1000
Permanent Ineff=
       F       F
Bank Sta=343.3,392.4
XS Rating Curve= 0 ,0
Exp/Cntr=0.3,0.1

Type RM Length L Ch R = 1 ,29.3    ,18.9,29.3,39.7
XS GIS Cut Line= 2
     1769739.987      282540.072     1769827.033      283386.794
#Sta/Elev= 30
       0 1025.61    19.6 1021.78    39.1 1016.23    78.3  1011.4   156.5  998.87
   195.7  993.77   215.2  992.91   244.6   994.1   264.2  994.16   313.1  992.87
   371.8  992.36   381.6  991.72   388.2990.1571   401.1  986.19   410.9   984.8
     450  984.91   459.8  985.85   489.2  992.15   528.3   998.1   547.9 1001.76
     587 1010.61   616.4 1019.85   655.5 1034.97   665.3  1038.1   675.1 1040.66
   704.4 1046.44     724 1051.23   753.4 1059.72   792.5 1072.21   851.2 1087.94
#Mann= 3 , 0 , 0
       0     .06       0   388.2    .045       0   459.8      .1       0
Bank Sta=388.2,459.8
XS Rating Curve= 0 ,0
Exp/Cntr=0.3,0.1

Chan Stop Cuts=-1
Use User Specified Reach Order=0
Composite Channel Slope=5